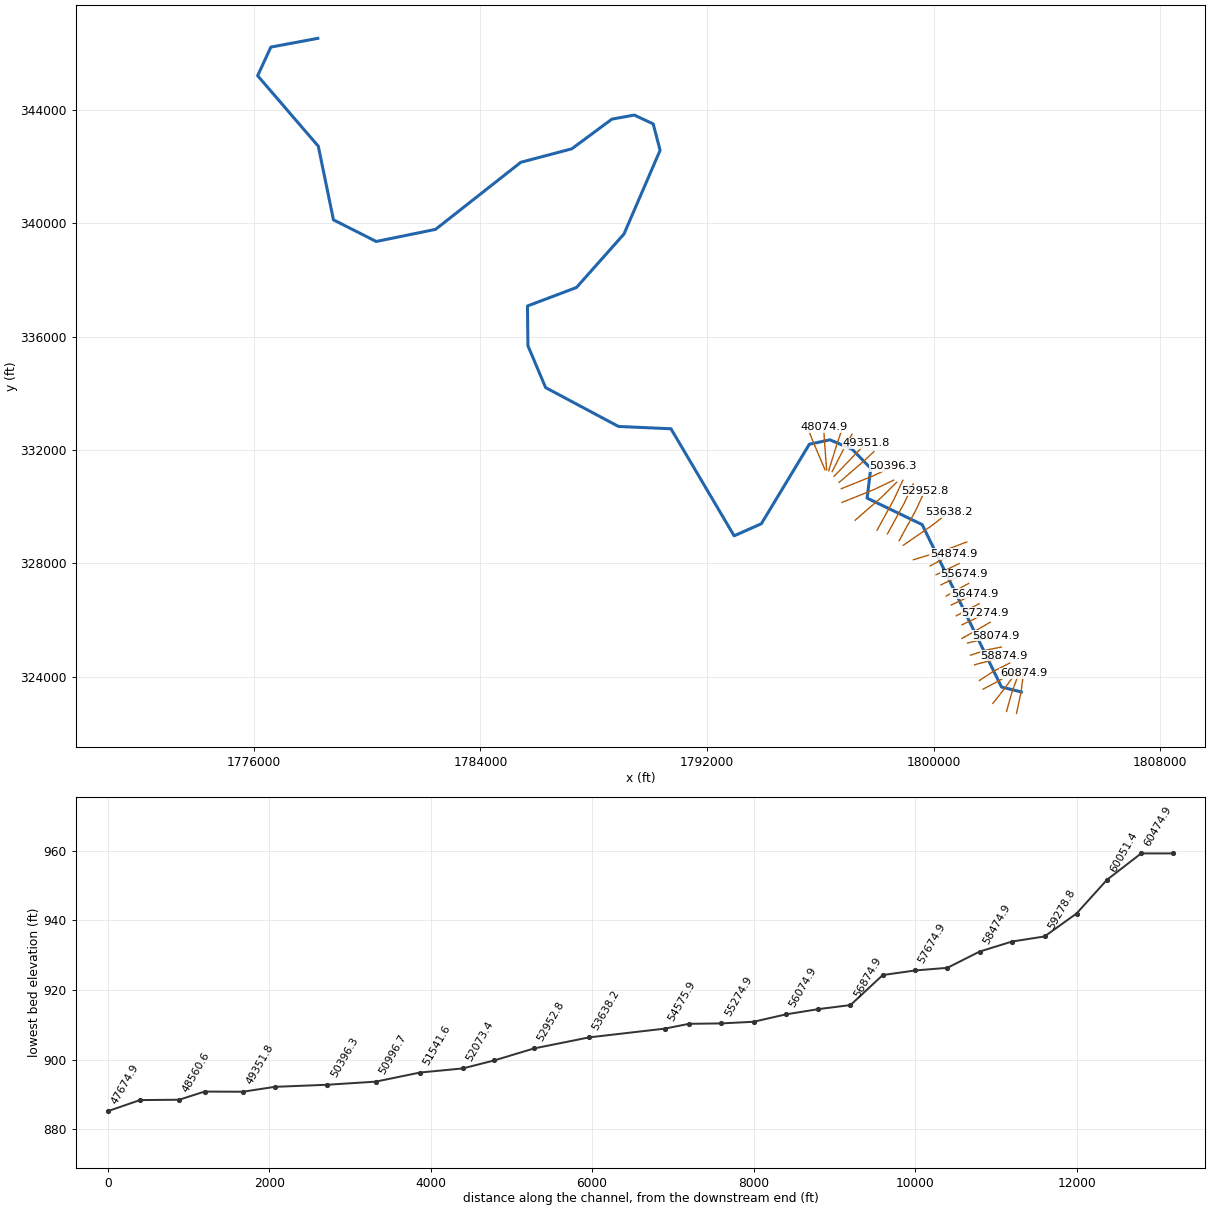
--- TygrtVlyRv.prj (project) ---

Proj Title=TygrtVlyRv
Current Plan=p01
Default Exp/Contr=0,0
English Units
Geom File=g01
Flow File=f01
Plan File=p01
BEGIN DESCRIPTION:
END DESCRIPTION:
DSS Export Rating Curves= 0
DSS Export Rating Curve Sorted= 0
DSS Export Volume Flow Curves= 0
DXF OffsetX= 0
DXF OffsetY= 0
DXF ScaleX= 0
DXF ScaleY= 0

--- TygrtVlyRv.p01 (plan) ---

Plan Title=Floodplain
Program Version=4.00
Geom File=g01
Flow File=f01
K Sum by GR=0
Std Step Tol=0.01
Critical Tol=0.01
Num of Std Step Trials=20
Max Error Tol=0.3
Flow Tol Ratio=0.001
Split Flow NTrial=30
Split Flow Tol=0.02
Split Flow Ratio=0.02
Log Output Level=0
Friction Slope Method=1
Unsteady Friction Slope Method=2
Unsteady Bridges Friction Slope Method=1
Global Log Level=0
CheckData=False
Run HTab=0
Run UNet=0
Run PostProcess=0
UNET Theta=0
UNET Theta Warmup=0
UNET ZTol=0
UNET ZSATol=0
UNET MxIter=0
UNET MaxInSteps=0
UNET DtIC=0
UNET DtMin=0
UNET MaxCRTS=0
UNET WFStab=0
UNET SFStab=0
UNET WFX=0
UNET SFX=0
UNET DSS MLevel=0
UNET DZMax Abort=0
UNET Convert EG Bridges=0
UNET Use Existing IB Tables=0
UNET Froude Limit=0
UNET Froude Power=0
Write IC File=0
Echo Input=False
Echo Output=False
Write Detailed=0

--- TygrtVlyRv.f01 (steady flow) ---

Flow Title=NFF Regression Equation
Program Version=4.00
Number of Profiles=1
Profile Names=P100yr
River Rch & RM=TygrtVlyRv,Main      ,60874.9
9462.630
River Rch & RM=TygrtVlyRv,Main      ,43326
10255.05
River Rch & RM=TygrtVlyRv,Main      ,42539.2
11256.88
River Rch & RM=TygrtVlyRv,Main      ,383.4
12315.01
River Rch & RM=TygrtVlyRv,Main      ,74.9
12324.26
Boundary for River Rch & Prof#=TygrtVlyRv,Main      ,1
Up Type=0
Dn Type=3
Dn Slope=0.000274

--- TygrtVlyRv.g01 (geometry) ---

Geom Title=USGS 3m DEM
Program Version=4.00

River Reach=TygrtVlyRv      ,Main
Reach XY= 30
     1803092.074      323463.406     1802391.719      323637.237
     1799590.697      329370.329      1797647.95      330305.644
     1797776.093      331356.299     1797117.887      332031.786
     1796334.472      332363.577     1795608.517      332206.336
     1793914.883      329401.341     1792953.983      328973.585
     1790724.357      332753.164     1788873.475      332834.339
     1786299.234      334207.008     1785675.407       335684.15
     1785659.798      337087.005      1787388.87      337739.494
     1789064.395      339625.046     1790340.845      342581.577
     1790097.692      343513.665     1789429.248      343825.264
     1788639.855      343682.471     1787223.858      342634.308
      1785425.18      342158.921     1782415.581      339791.269
     1780320.674      339364.028       1778811.6      340126.921
     1778276.597      342725.824     1776135.411      345214.991
     1776601.513      346224.827     1778260.517       346534.05

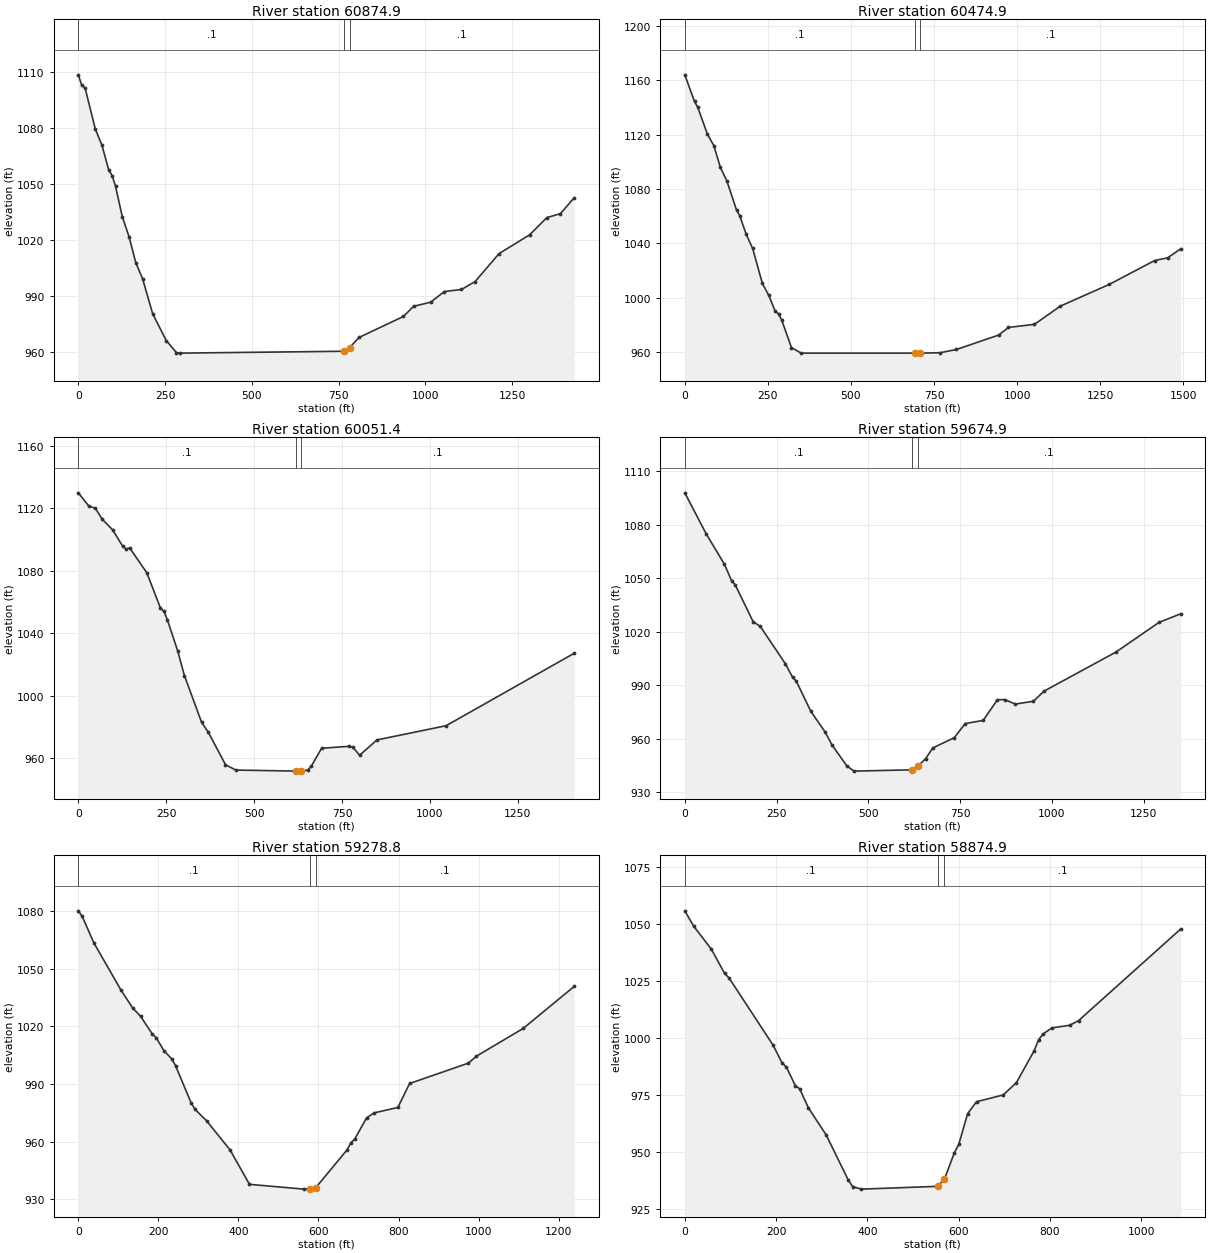
Type RM Length L Ch R = 1 ,60874.9 ,399.698,400,390.136
XS GIS Cut Line= 3
     1802921.342      322707.183     1803082.167      323464.362
     1803165.555      324118.191
#Sta/Elev= 30
       0 1108.63     9.7 1103.09    19.5 1101.54    48.7 1079.67    68.2 1070.73
    87.6 1057.47    97.4 1054.55   107.1 1048.82   126.6 1032.48   146.1 1021.68
   165.5 1007.73     185  999.18   214.2   980.3   253.2  965.95   282.4  959.48
   292.1  959.17   766.6  960.17   781.6  962.16   808.6  967.59   936.5  978.86
     966  984.32  1015.2  986.54  1054.5  992.24  1103.7  993.35  1143.1  997.62
  1211.9 1012.59  1300.5 1022.76  1349.6 1031.94    1389 1034.09  1428.4  1042.6
#Mann= 3 , 0 , 0
       0      .1       0   766.6    .045       0   781.6      .1       0
Bank Sta=766.6,781.6
XS Rating Curve= 0 ,0
Exp/Cntr=0.3,0.1

Type RM Length L Ch R = 1 ,60474.9 ,428.118,423.405,420.471
XS GIS Cut Line= 3
      1802568.59       322775.02      1802757.47      323449.261
     1803029.881      324192.812
#Sta/Elev= 30
       0 1163.98    29.2 1144.38    38.9 1140.14    68.1 1120.26    87.5 1111.85
     107 1095.84   126.4 1086.03   155.6 1064.53   165.3 1060.24   184.8 1046.67
   204.2 1036.17   233.4  1010.5   252.8 1001.63   272.3  989.83     282  988.16
   291.7  983.49   320.9  963.28   350.1  959.17   692.7  959.17   707.7  959.17
   768.6  959.47   817.5  961.85   944.6  972.47   973.9  978.07  1052.1  980.35
  1130.4  993.79    1277  1009.7  1413.9  1027.3    1453 1029.31  1492.1  1035.9
#Mann= 3 , 0 , 0
       0      .1       0   692.7    .045       0   707.7      .1       0
Bank Sta=692.7,707.7
XS Rating Curve= 0 ,0
Exp/Cntr=0.3,0.1

Type RM Length L Ch R = 1 ,60051.4 ,385.615,376.595,368.796
XS GIS Cut Line= 3
     1802086.948      323059.935     1802473.618      323548.361
      1802934.91      324186.028
#Sta/Elev= 30
       0 1129.75    29.2 1121.42    48.7 1119.76    68.1 1112.81    97.3 1106.11
   126.5 1095.48   136.3 1093.67     146  1094.5   194.7 1078.57   233.6 1055.98
   243.3 1053.91   253.1 1048.53   282.3 1028.74   301.7 1012.71   350.4  982.93
   369.9  976.35   418.5  955.72   447.7  952.27   619.4  951.62     623  951.59
   634.4  951.66   652.5  952.23   662.3  954.69   691.8  966.24   770.5  967.49
   780.4  966.98     800  961.77   849.2  971.56    1046  980.68    1410 1027.02
#Mann= 3 , 0 , 0
       0      .1       0   619.4    .045       0   634.4      .1       0
Bank Sta=619.4,634.4
XS Rating Curve= 0 ,0
Exp/Cntr=0.3,0.1

Type RM Length L Ch R = 1 ,59674.9 ,393.827,396.028,394.319
XS GIS Cut Line= 3
      1801740.98      323561.929     1802295.057      323854.865
     1802907.775      324240.298
#Sta/Elev= 30
       0 1097.77    58.8  1074.6   107.7 1057.85   127.3 1048.62   137.1 1046.34
   186.1 1025.64   205.7 1022.96   274.2 1001.99   293.8   994.4   303.6  992.37
   342.8  975.59   381.9  963.91   401.5  956.41   440.7  945.04   460.3  941.92
   619.2  942.66   634.2  944.54   656.1  948.92   675.7  954.94   734.3  960.67
   763.7  968.56   812.6   970.3   851.7  981.93   871.3  981.95   900.6  979.47
   949.6  981.06   978.9  986.75  1174.5  1008.6  1291.9 1025.23  1350.6 1030.01
#Mann= 3 , 0 , 0
       0      .1       0   619.2    .045       0   634.2      .1       0
Bank Sta=619.2,634.2
XS Rating Curve= 0 ,0
Exp/Cntr=0.3,0.1

Type RM Length L Ch R = 1 ,59278.8 ,411.466,403.972,400.274
XS GIS Cut Line= 3
     1801612.089      323867.195     1802107.839      324192.182
     1802683.913      324484.511
#Sta/Elev= 30
       0 1080.07     9.7 1077.16    38.9 1063.38   106.9 1038.72     136 1029.49
   155.5 1025.26   184.6 1016.06   194.4 1014.11   213.8 1007.39   233.2 1003.07
   242.9  999.55   281.8  980.21   291.5  976.84   320.7   970.8     379  955.76
   427.6  937.83   563.6  935.34   578.2  935.54   593.2  936.09   671.1  955.69
   680.9  959.43   690.7  961.41     720  972.35   739.6  975.02   798.3  977.81
   827.7  990.28   974.5 1000.86   994.1 1004.41  1111.5 1018.91  1238.8 1040.74
#Mann= 3 , 0 , 0
       0      .1       0   578.2    .045       0   593.2      .1       0
Bank Sta=578.2,593.2
XS Rating Curve= 0 ,0
Exp/Cntr=0.3,0.1

Type RM Length L Ch R = 1 ,58874.9 ,398.719,400,396.615
XS GIS Cut Line= 3
     1801442.497      324423.458     1801985.713      324565.989
     1802480.402      324742.291
#Sta/Elev= 30
       0 1055.62    19.4 1048.92    58.1 1038.88    87.1 1028.29    96.8 1026.31
   193.7  996.79     213  989.14   222.7  987.29   242.1   979.2   251.8  977.77
   271.1  969.37   309.9  957.59   358.3  937.85   367.9  934.96   387.3  933.87
   554.1  935.09   569.1  938.24   590.8  949.75   600.5  953.45     620  966.92
   639.4   972.1   697.8  975.07   726.9  980.46   765.8  994.42   775.6  999.26
   785.3 1001.75   804.7 1004.41   843.6 1005.55   863.1 1007.59  1086.8 1047.64
#Mann= 3 , 0 , 0
       0      .1       0   554.1    .045       0   569.1      .1       0
Bank Sta=554.1,569.1
XS Rating Curve= 0 ,0
Exp/Cntr=0.3,0.1

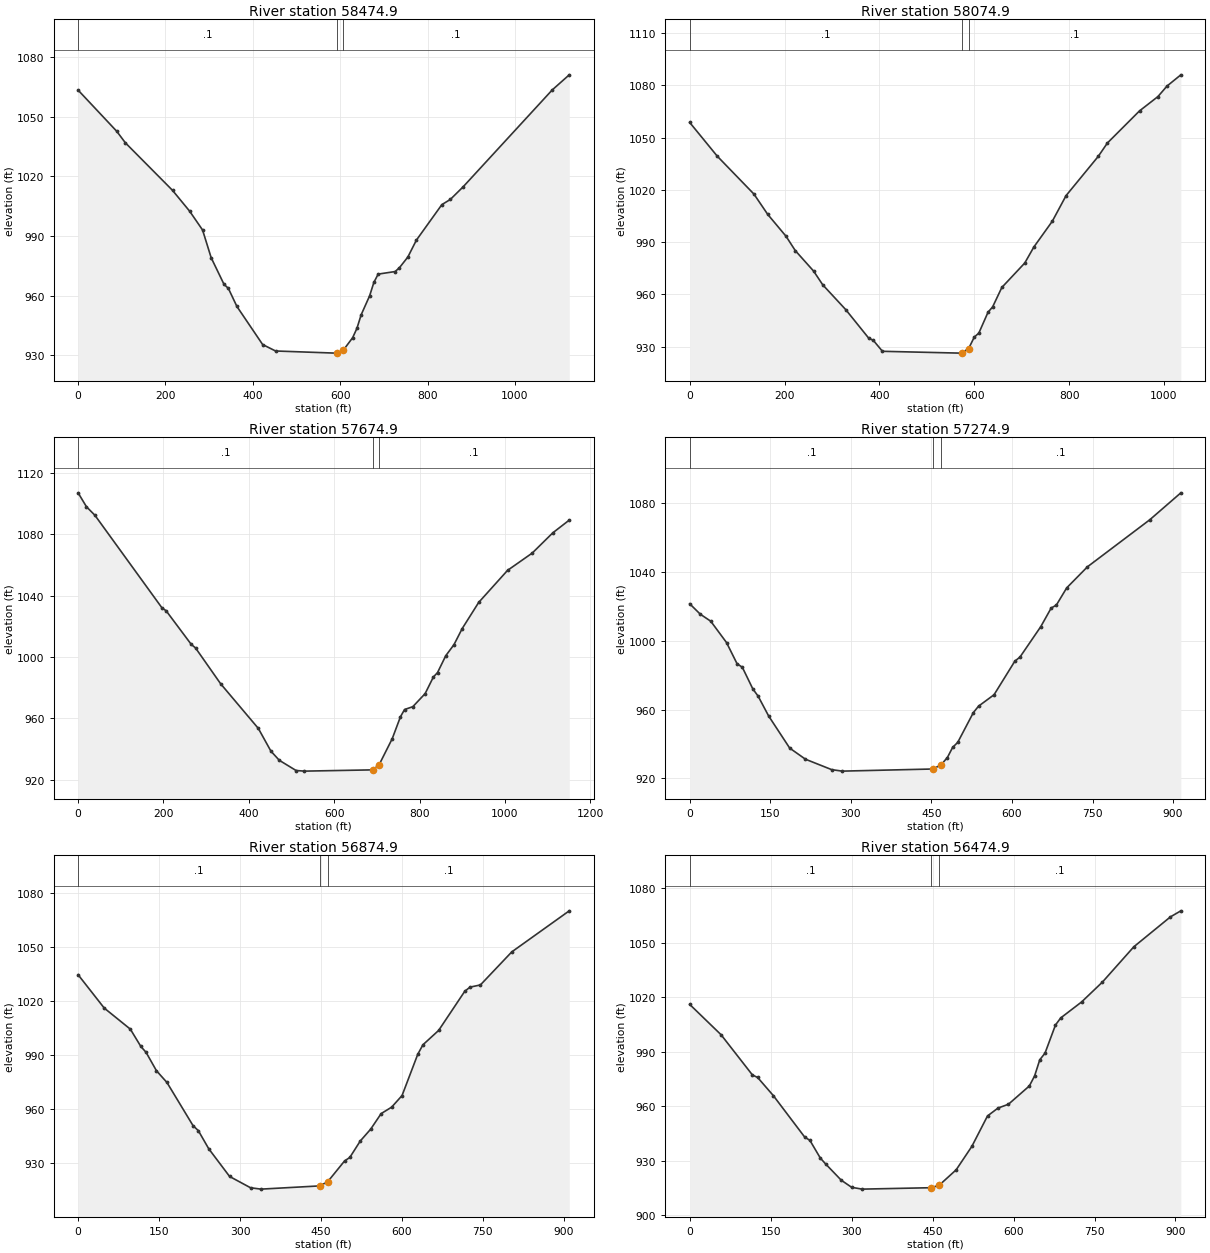
Type RM Length L Ch R = 1 ,58474.9 ,401.667,400,401.617
XS GIS Cut Line= 3
     1801300.039      324762.642     1801870.239      324947.065
      1802385.43      325047.557
#Sta/Elev= 30
       0 1063.44    88.4 1042.72   108.1 1036.93   216.1 1012.97   255.4 1002.45
   284.9     993   304.6  979.03     334  965.63   343.9  963.62   363.5   954.5
   422.4  935.33   451.9  932.08   589.5     931   591.8  931.05   606.8  932.42
   628.4  938.77   638.2  943.47   647.9  950.31   667.3  959.88     677  966.62
   686.8  970.79   725.6  972.08   735.4  973.98   754.8   979.4   774.2  987.86
   832.6 1005.78     852 1008.39   881.2 1014.72  1085.3 1063.55  1124.2 1071.14
#Mann= 3 , 0 , 0
       0      .1       0   591.8    .045       0   606.8      .1       0
Bank Sta=591.8,606.8
XS Rating Curve= 0 ,0
Exp/Cntr=0.3,0.1

Type RM Length L Ch R = 1 ,58074.9 ,393.785,400,406.034
XS GIS Cut Line= 3
       1801191.5      325190.015     1801755.494      325327.971
     1802194.694      325446.829
#Sta/Elev= 30
       0 1058.76    58.1  1039.4   135.5 1017.63   164.5 1005.99   203.2   993.4
   222.6   985.2   261.3  973.42   280.6  965.52     329  951.31   377.4  934.94
   387.1  933.68   406.4  927.38   570.9  926.33   573.1  926.42   588.1  928.95
     600  935.51   609.7  937.86     629   949.8   638.7  952.85   658.1  964.02
   706.5  978.07   725.8  987.31   764.6 1002.07   793.6 1016.77   861.4 1039.27
   880.7 1046.95   948.5 1065.41   987.2  1073.6  1006.6 1079.69  1035.6  1086.1
#Mann= 3 , 0 , 0
       0      .1       0   573.1    .045       0   588.1      .1       0
Bank Sta=573.1,588.1
XS Rating Curve= 0 ,0
Exp/Cntr=0.3,0.1

Type RM Length L Ch R = 1 ,57674.9 ,402.216,400,399.476
XS GIS Cut Line= 3
     1800993.643      325350.939     1801600.313      325694.504
     1801991.081       325924.31
#Sta/Elev= 30
       0 1106.99    19.6 1097.91    39.3 1092.39   196.4 1032.02   206.2 1030.11
   265.1 1008.17     275  1005.9   333.9  982.51   422.2   953.4   451.7  938.58
   471.3  932.63   510.6  925.97   530.3  925.57   689.7  926.39   704.7   929.5
   735.8   946.7   755.1     961   764.7  965.74     784  967.57   812.9   976.1
   832.2  986.92   841.9  989.79   861.2 1000.79   880.5 1008.03   899.8 1018.54
   938.3 1035.53  1005.9 1056.43  1063.7  1067.7  1111.9  1080.9  1150.5 1089.21
#Mann= 3 , 0 , 0
       0      .1       0   689.7    .045       0   704.7      .1       0
Bank Sta=689.7,704.7
XS Rating Curve= 0 ,0
Exp/Cntr=0.3,0.1

Type RM Length L Ch R = 1 ,57274.9 ,398.776,400,399.163
XS GIS Cut Line= 3
     1800997.115      325835.477      1801414.95      326029.015
     1801807.816      326256.616
#Sta/Elev= 30
       0 1021.57    19.6 1015.53    39.2 1011.42    68.6     999    88.2  986.69
      98  984.64   117.6  972.03   127.4  967.85     147  956.31   186.2  937.65
   215.5  931.19   264.5  925.11   284.1  924.26     453   925.5     468  927.92
   479.8  932.17   489.5  938.02   499.1  941.01   528.1  958.26   537.8  962.03
   566.7  968.68   605.4  988.19     615   990.6   653.7 1008.28     673 1019.06
   682.7 1020.81     702 1030.82   740.6 1043.06   856.6  1070.4   914.5 1086.07
#Mann= 3 , 0 , 0
       0      .1       0     453    .045       0     468      .1       0
Bank Sta=453,468
XS Rating Curve= 0 ,0
Exp/Cntr=0.3,0.1

Type RM Length L Ch R = 1 ,56874.9 ,400.951,400,399.241
XS GIS Cut Line= 3
     1800798.909      326153.092     1801200.839      326366.345
     1801602.769      326579.599
#Sta/Elev= 30
       0 1034.71    48.4  1016.2    96.8 1004.48   116.2   994.9   125.9  991.62
   145.2  981.38   164.6  974.88     213  950.88   222.7  948.15     242  938.08
   280.7  922.67   319.5   916.4   338.8  915.64   447.5  917.43   462.5  919.77
   493.7  931.29   503.4  933.23   522.8  942.37   542.1  948.96   561.5  957.59
   580.9  961.17   600.2  967.61   629.3  990.52   638.9  995.81     668 1003.78
   716.4 1025.52   726.1 1027.82   745.4 1029.04   803.5 1047.39     910  1070.2
#Mann= 3 , 0 , 0
       0      .1       0   447.5    .045       0   462.5      .1       0
Bank Sta=447.5,462.5
XS Rating Curve= 0 ,0
Exp/Cntr=0.3,0.1

Type RM Length L Ch R = 1 ,56474.9 ,398.241,400,401.052
XS GIS Cut Line= 3
     1800618.506      326531.127     1801029.095      326727.238
     1801437.973       326926.84
#Sta/Elev= 30
       0 1015.99    58.1  999.32   116.2  977.22   125.9  975.82   154.9  965.88
     213   943.1   222.7  941.27     242  931.55   251.7  928.35   280.8  919.37
   300.1  915.46   319.5  914.47   447.5  915.25   462.5  916.68   493.7  925.08
   522.8  937.98   551.8   954.7   571.2  959.01   590.6  961.12   629.3  971.17
     639  976.65   648.6  985.55   658.3  989.19   677.7 1004.67   687.4 1008.55
   726.1 1017.33   764.8 1028.29   822.9 1047.66   890.7 1064.09     910 1067.41
#Mann= 3 , 0 , 0
       0      .1       0   447.5    .045       0   462.5      .1       0
Bank Sta=447.5,462.5
XS Rating Curve= 0 ,0
Exp/Cntr=0.3,0.1

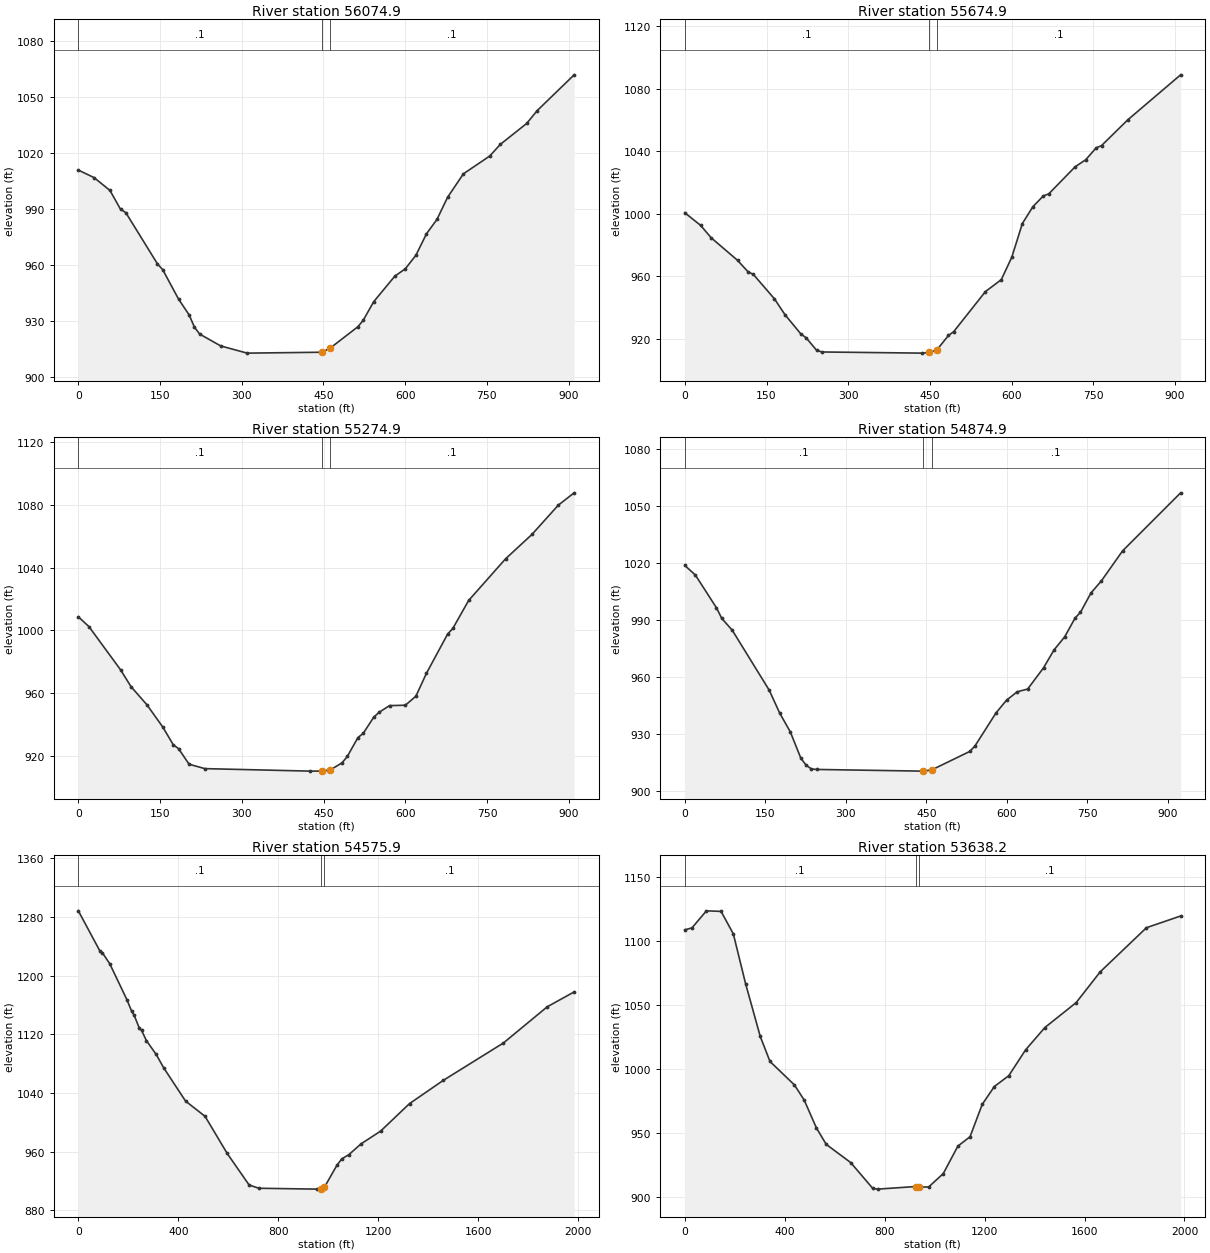
Type RM Length L Ch R = 1 ,56074.9 ,401.903,400,398.097
XS GIS Cut Line= 3
     1800437.814      326847.251     1800831.828      327074.747
     1801231.082      327293.271
#Sta/Elev= 30
       0 1010.86      29 1006.81    58.1  999.95    77.4  989.92    87.1  988.12
   145.2  960.72   154.9  957.59   183.9  941.89   203.3  933.44     213  926.94
   222.6  923.18   261.4  916.81   309.8  912.97   447.5  913.45   462.5  915.71
   513.1  927.08   522.8  930.47   542.1  940.45   580.9  954.12   600.2  958.08
   619.6  965.29     639  976.77   658.3  984.48   677.7  996.27   706.8 1008.86
   755.2 1018.38   774.5 1024.58     823  1035.8   842.3 1042.67   910.1 1061.79
#Mann= 3 , 0 , 0
       0      .1       0   447.5    .045       0   462.5      .1       0
Bank Sta=447.5,462.5
XS Rating Curve= 0 ,0
Exp/Cntr=0.3,0.1

Type RM Length L Ch R = 1 ,55674.9 ,399.744,400,400.77
XS GIS Cut Line= 3
      1800252.57      327244.501      1800664.38      327437.928
     1801080.651      327621.977
#Sta/Elev= 30
       0  1000.6      29  992.53    48.4  984.59    96.8  970.19   116.2  962.81
   125.8  961.19   164.6  945.54   183.9  935.41     213  923.13   222.6  920.69
     242  912.67   251.7  911.59   435.6  910.85   447.5  911.26   462.5  912.86
     484  922.14   493.7  924.64   551.8  950.19   580.9  957.81   600.2  972.16
   619.6   993.7     639 1004.51   658.3 1011.42     668 1012.64   716.4 1029.95
   735.8 1034.45   755.2  1042.1   764.9 1043.52   813.3 1060.06   910.1 1088.76
#Mann= 3 , 0 , 0
       0      .1       0   447.5    .045       0   462.5      .1       0
Bank Sta=447.5,462.5
XS Rating Curve= 0 ,0
Exp/Cntr=0.3,0.1

Type RM Length L Ch R = 1 ,55274.9 ,399.089,400,400.161
XS GIS Cut Line= 3
      1800083.01      327600.251     1800492.623      327798.346
     1800902.237      327996.441
#Sta/Elev= 30
       0 1008.65    19.4 1002.46    77.4  974.96    96.8  964.14   125.9  952.62
   154.9   938.5   174.3  927.15   183.9  924.71   203.3  914.77   232.3  911.97
     426  910.38   447.5  910.42   462.5  911.18     484  915.66   493.7  919.75
   513.1  931.73   522.8  934.41   542.1  944.68   551.8  947.81   571.2  952.11
   600.2  952.34   619.6  958.14   638.9  972.68   677.7  997.63   687.3 1001.23
   716.4 1019.09   784.1 1045.59   832.6 1061.13     881  1079.8     910 1087.61
#Mann= 3 , 0 , 0
       0      .1       0   447.5    .045       0   462.5      .1       0
Bank Sta=447.5,462.5
XS Rating Curve= 0 ,0
Exp/Cntr=0.3,0.1

Type RM Length L Ch R = 1 ,54874.9 ,303.339,298.972,295.354
XS GIS Cut Line= 3
     1799872.331      327911.613     1800270.959      328124.684
      1800693.92      328333.009
#Sta/Elev= 30
       0 1018.68    19.7 1013.62      59  996.34    68.8  990.79    88.4  984.52
   157.2  952.95   176.9  940.77   196.5  930.96   216.2  917.04     226   913.4
   235.8   911.4   245.7  911.15   442.2  910.26   444.5   910.3   459.5  910.85
   530.6  920.62   540.4  923.51   579.7  940.96   599.3  947.67     619  952.06
   638.6  953.53   668.1  964.69   687.7  974.14   707.4  980.99     727  990.97
   736.9  993.97   756.5 1004.15   776.1 1010.61   815.4 1026.36   923.5 1056.95
#Mann= 3 , 0 , 0
       0      .1       0   444.5    .045       0   459.5      .1       0
Bank Sta=444.5,459.5
XS Rating Curve= 0 ,0
Exp/Cntr=0.3,0.1

Type RM Length L Ch R = 1 ,54575.9 ,930.858,937.657,944.456
XS GIS Cut Line= 6
     1799280.598      328129.114     1799344.687      328148.774
     1800008.937      328352.539     1800455.845      328489.633
      1800879.43      328649.647     1801162.385      328756.536
#Sta/Elev= 30
       0 1288.29    86.6 1233.36    96.4 1231.08   125.8 1216.08   194.3 1167.26
   213.8 1151.13   223.6 1145.85   243.2 1129.11     253 1125.41   272.5 1111.35
   311.7 1092.48     341 1074.63   429.1 1028.95   507.4 1008.08   595.5   957.7
   683.6  914.53   722.7  910.07   956.6  908.88   970.2   909.2   985.2  911.62
  1034.5  941.11    1054  949.98  1083.2  956.02  1131.9  970.68  1209.8  987.94
  1325.6 1025.48  1460.5  1057.1  1701.6 1108.16  1877.2 1157.55  1984.6 1177.74
#Mann= 3 , 0 , 0
       0      .1       0   970.2    .045       0   985.2      .1       0
Bank Sta=970.2,985.2
XS Rating Curve= 0 ,0
Exp/Cntr=0.3,0.1

Type RM Length L Ch R = 1 ,53638.2 ,675.575,685.398,695.221
XS GIS Cut Line= 6
     1798924.645      328641.276     1798979.857      328679.297
       1799552.1       329073.36     1799937.106      329338.487
     1800292.977       329618.46     1800530.698      329805.482
#Sta/Elev= 30
       0 1108.99    28.7 1110.54    86.6 1123.86   145.3 1123.41   194.3 1105.81
   243.2 1067.03   301.9 1025.77     341 1006.14   438.9   987.8     478  975.93
     527  954.14   566.1  941.34     664  927.14   752.1     907   771.6  906.37
   923.8  908.39   938.8  907.95   976.1  908.06  1034.5  918.51    1093  939.98
  1141.7  947.31  1190.3  972.52  1238.9  986.54  1296.7  995.02  1364.2 1015.23
  1441.3 1032.66  1566.5 1052.14  1662.8 1076.19    1848 1110.69  1984.6 1119.82
#Mann= 3 , 0 , 0
       0      .1       0   923.8    .045       0   938.8      .1       0
Bank Sta=923.8,938.8
XS Rating Curve= 0 ,0
Exp/Cntr=0.3,0.1

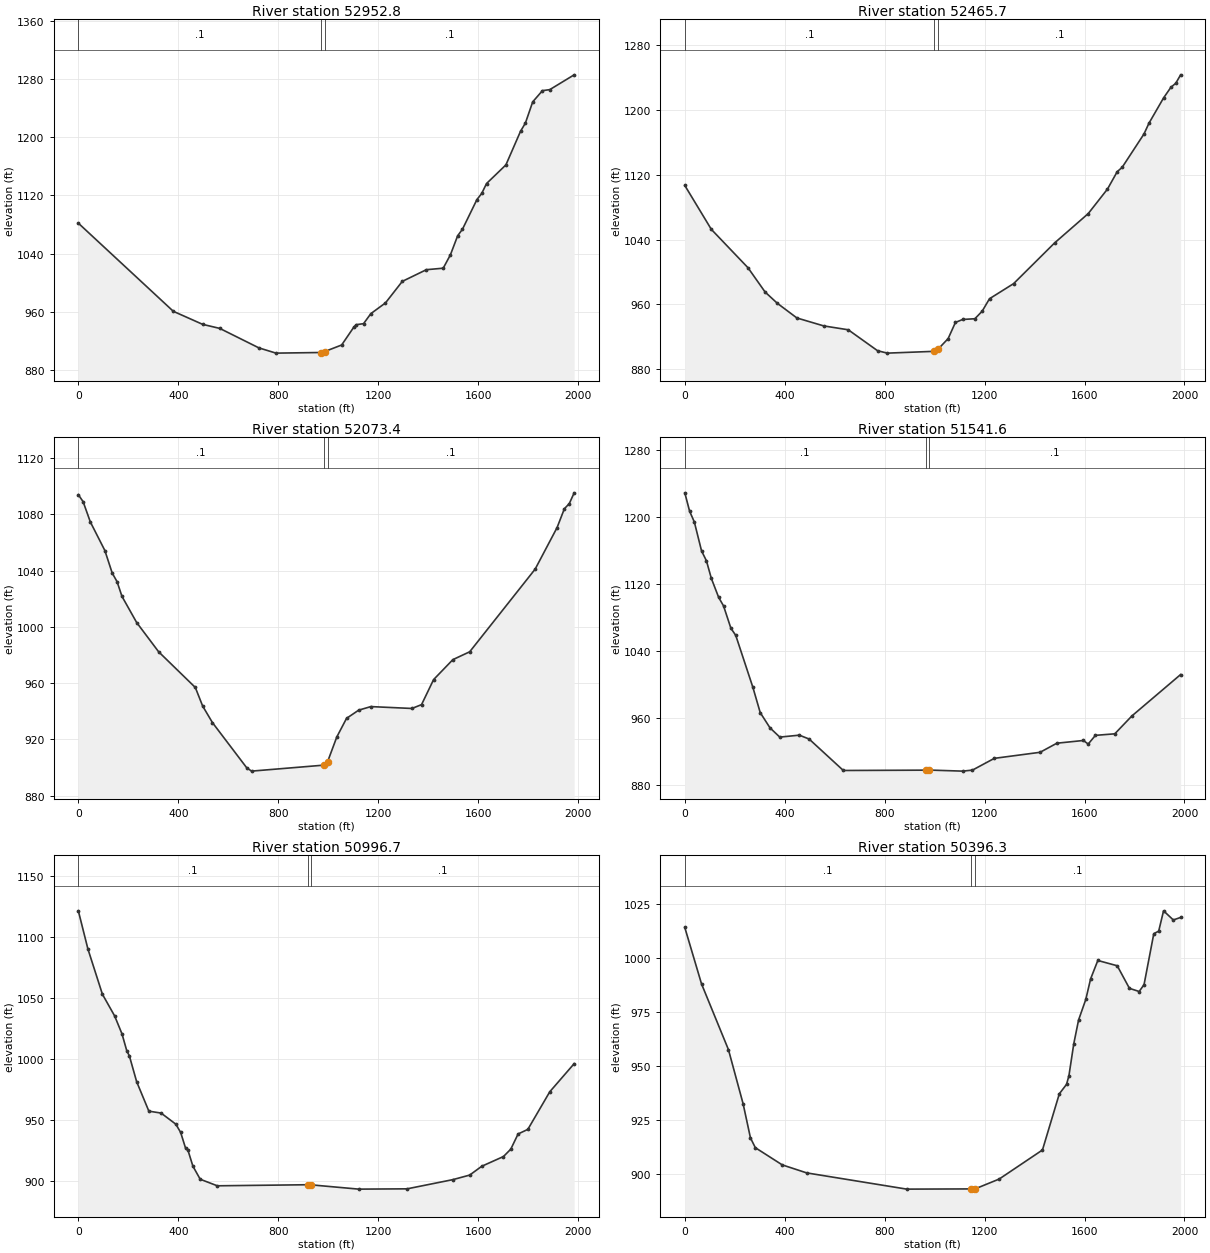
Type RM Length L Ch R = 1 ,52952.8 ,487.415,487.154,486.892
XS GIS Cut Line= 6
     1798779.283      328803.828     1798811.439      328862.649
     1799144.718        329472.3     1799368.948      329882.474
     1799560.477      330292.772     1799688.419      330566.852
#Sta/Elev= 30
       0 1081.79   380.2  960.65   497.6  942.72   566.1  937.15   722.7  910.39
   791.1  903.18   970.6  904.04   985.6  905.28    1054  914.36  1102.7   938.9
  1112.4  942.26  1141.7  943.69  1170.9  957.48  1229.3  972.16  1296.7 1001.78
  1393.1 1017.84  1460.5  1019.9  1489.4 1038.37  1518.3 1064.46  1537.6 1073.49
  1595.4 1114.19  1614.7 1122.68  1633.9 1136.24  1711.4 1161.86  1769.9 1208.01
  1789.4 1219.32  1818.7  1248.5  1857.7  1263.9    1887 1265.29  1984.6 1285.64
#Mann= 3 , 0 , 0
       0      .1       0   970.6    .045       0   985.6      .1       0
Bank Sta=970.6,985.6
XS Rating Curve= 0 ,0
Exp/Cntr=0.3,0.1

Type RM Length L Ch R = 1 ,52465.7 ,392.226,392.319,392.412
XS GIS Cut Line= 6
     1798365.112      329042.773     1798397.268      329101.594
     1798730.546      329711.245     1798954.776      330121.419
     1799146.306      330531.717     1799274.248      330805.797
#Sta/Elev= 30
       0 1106.73   106.2 1052.53     253 1005.13   321.5  975.17   370.4  961.27
   448.7  943.16   556.3  933.35   654.2  928.58   771.6  902.74   810.5  899.77
   998.2  901.98  1013.2  904.46    1054  917.68  1083.2  937.64  1112.4  941.33
  1161.1  942.21  1190.3  951.54  1219.6  966.91    1316  985.53  1479.8 1035.67
  1614.7 1071.96  1691.9  1102.3  1730.9 1123.78  1750.4    1129  1838.2 1170.39
  1857.7 1183.47  1916.3 1214.74  1945.5  1227.8  1965.1 1232.85  1984.6 1243.27
#Mann= 3 , 0 , 0
       0      .1       0   998.2    .045       0  1013.2      .1       0
Bank Sta=998.2,1013.2
XS Rating Curve= 0 ,0
Exp/Cntr=0.3,0.1

Type RM Length L Ch R = 1 ,52073.4 ,541.196,531.794,522.393
XS GIS Cut Line= 6
     1797998.729       329170.21     1798030.885      329229.032
     1798364.163      329838.682     1798588.394      330248.856
     1798779.923      330659.155     1798907.865      330933.234
#Sta/Elev= 30
       0  1093.9    19.2 1088.93    47.9  1074.6   106.2 1054.23   135.5 1038.25
   155.1 1032.06   174.7 1021.63   233.4 1003.08   321.5  982.25   468.3   956.9
   497.6  943.72   536.8  931.94   673.8  899.88   693.3  897.46   982.5  901.71
   997.5  904.04  1034.5  921.71  1073.5  934.95  1122.2   940.8  1170.9  943.32
  1335.3  941.99  1373.8  944.73    1422  962.51  1499.1  976.69  1566.5  982.27
  1828.5 1041.02  1916.3 1070.55  1945.5 1083.94  1965.1 1087.57  1984.6 1095.23
#Mann= 3 , 0 , 0
       0      .1       0   982.5    .045       0   997.5      .1       0
Bank Sta=982.5,997.5
XS Rating Curve= 0 ,0
Exp/Cntr=0.3,0.1

Type RM Length L Ch R = 1 ,51541.6 ,550.131,544.881,540.886
XS GIS Cut Line= 6
     1797227.272      329526.082     1797277.841      329570.091
     1797801.958      330026.215     1798154.584      330333.097
     1798476.586      330651.442     1798691.683      330864.096
#Sta/Elev= 30
       0 1229.32    19.2 1207.38    38.3 1194.31      67 1159.88    86.6 1147.97
   106.2 1126.96   135.5 1104.23   155.1 1093.97   184.5 1067.28     204 1058.67
   272.5  996.57   301.9  966.29     341  948.07   380.2  936.99   458.5  939.31
   497.6  934.68   634.6  897.04   963.8  897.43   978.8  897.53  1112.4  896.27
  1151.4  897.49  1238.9  911.56    1422   918.8  1489.4   929.7  1595.4  932.94
  1614.7  928.68  1643.6  939.08  1721.1  940.92  1789.4  962.27  1984.6 1011.87
#Mann= 3 , 0 , 0
       0      .1       0   963.8    .045       0   978.8      .1       0
Bank Sta=963.8,978.8
XS Rating Curve= 0 ,0
Exp/Cntr=0.3,0.1

Type RM Length L Ch R = 1 ,50996.7 ,600.155,600.38,599.35
XS GIS Cut Line= 6
     1796762.172      330152.406     1796824.343      330177.482
     1797468.702      330437.385     1797902.228      330612.248
     1798310.553       330807.95     1798583.314      330938.678
#Sta/Elev= 30
       0 1121.21    38.3 1090.04    96.4    1053   145.3 1035.28   174.7 1020.64
   194.3  1006.5     204 1002.82   233.4  981.52   282.3  957.42   331.3  955.85
     390  946.81   409.5  940.08   429.1  927.22   438.9   925.4   458.5  912.47
   487.8  901.75   556.3  896.39   917.6  897.26   932.6  897.15  1122.2  893.67
    1316  893.91  1499.1  901.43  1566.5  905.16  1614.7  912.36  1701.6  920.32
  1730.9  926.34  1760.2  938.77  1799.2  942.52    1887  973.26  1984.6  996.26
#Mann= 3 , 0 , 0
       0      .1       0   917.6    .045       0   932.6      .1       0
Bank Sta=917.6,932.6
XS Rating Curve= 0 ,0
Exp/Cntr=0.3,0.1

Type RM Length L Ch R = 1 ,50396.3 ,644.238,651.635,659.031
XS GIS Cut Line= 6
     1796734.885      330636.138     1796797.055      330661.215
     1797441.414      330921.117      1797874.94       331095.98
     1798283.265      331291.682     1798556.027      331422.411
#Sta/Elev= 30
       0 1014.29      67  988.08   174.7  957.56   233.4  932.42   262.8  916.56
   282.3  912.02     390  904.03   487.8  900.31   888.4  892.77  1146.5  892.87
  1161.5  892.87  1258.2  897.44  1431.6  910.95  1499.1  937.05    1528  941.44
  1537.6  945.49  1556.9  960.27  1576.1  971.31    1605  980.87  1624.3  990.42
  1653.2  998.97  1730.9  996.51  1779.7  986.03  1818.7  984.56  1838.2  987.75
  1877.2 1011.42  1896.8 1012.59  1916.3 1022.03  1955.3 1017.79  1984.6 1018.96
#Mann= 3 , 0 , 0
       0      .1       0  1146.5    .045       0  1161.5      .1       0
Bank Sta=1146.5,1161.5
XS Rating Curve= 0 ,0
Exp/Cntr=0.3,0.1

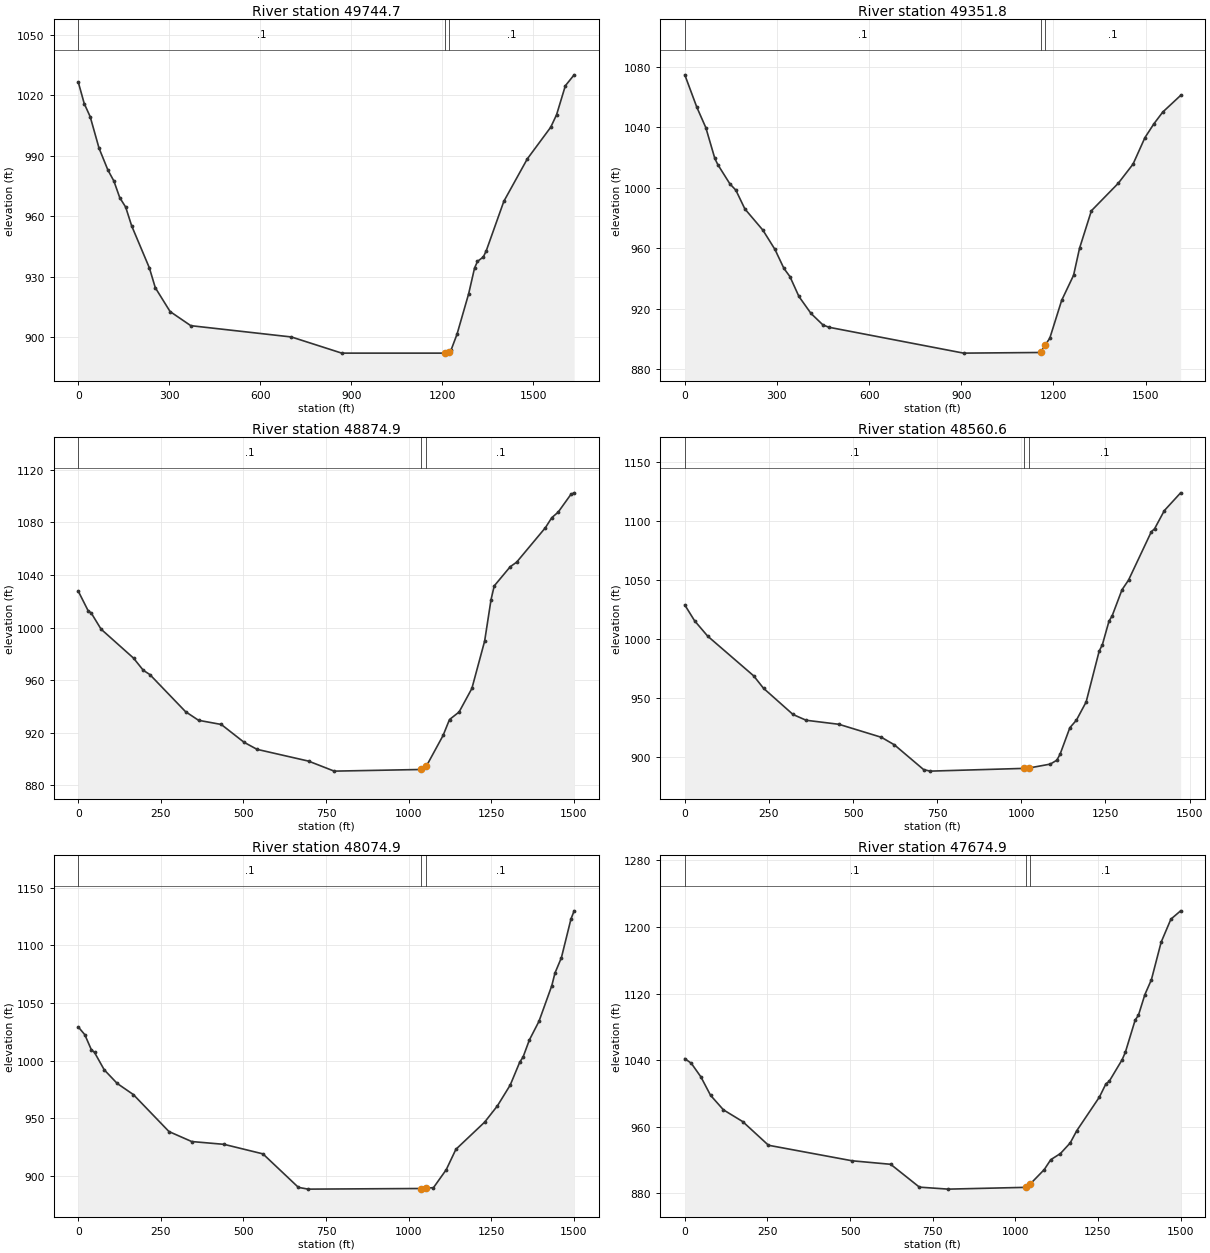
Type RM Length L Ch R = 1 ,49744.7 ,391.91,392.854,393.797
XS GIS Cut Line= 4
     1796659.423      330860.665     1797206.976      331332.146
     1797554.688       331631.55     1797883.903      331944.639
#Sta/Elev= 30
       0 1026.51    19.5 1015.95    39.1 1009.46    68.4   993.8    97.6  982.98
   117.2  977.58   136.7  969.27   156.2  964.61   175.8  955.36   234.3  934.48
   253.9  924.62   302.7   912.8     371  905.79     703  900.18     869  892.17
    1208  892.17    1223  892.71  1229.8  893.78  1249.1  901.48  1287.8   921.7
  1307.1  934.37  1316.8  937.67  1336.1  939.89  1345.8  942.99  1403.8  967.51
  1481.1  988.52  1558.4 1004.24  1577.7 1010.43  1606.7 1024.83  1635.7 1030.23
#Mann= 3 , 0 , 0
       0      .1       0    1208    .045       0    1223      .1       0
Bank Sta=1208,1223
XS Rating Curve= 0 ,0
Exp/Cntr=0.3,0.1

Type RM Length L Ch R = 1 ,49351.8 ,470.339,476.957,482.187
XS GIS Cut Line= 4
     1796482.932       331075.64     1796970.452      331583.758
     1797285.462      331912.078     1797600.472      332240.397
#Sta/Elev= 30
       0 1074.57    39.1 1053.21    68.5 1039.67    97.8 1019.32   107.6 1015.23
   146.7 1002.59   166.3  998.37   195.6     986   254.3  971.98   293.4  959.29
   322.7  946.73   342.3  941.32   371.6  928.17   410.8  916.99   449.9  909.37
   469.4  907.85   907.5  890.77  1158.3  891.19  1173.3  896.16  1188.2  900.59
  1226.9  925.62  1265.7  942.19    1285  959.94  1323.7  984.79  1410.9 1002.89
  1459.3 1015.61    1498 1033.09    1527 1042.17  1556.1    1050  1614.2 1060.97
#Mann= 3 , 0 , 0
       0      .1       0  1158.3    .045       0  1173.3      .1       0
Bank Sta=1158.3,1173.3
XS Rating Curve= 0 ,0
Exp/Cntr=0.3,0.1

Type RM Length L Ch R = 1 ,48874.9 ,310.671,314.255,318.775
XS GIS Cut Line= 4
     1796411.028      331237.352     1796678.927      331763.238
     1796885.937      332169.599     1797116.952      332561.374
#Sta/Elev= 30
       0 1027.58    29.5 1012.88    39.3 1010.94    68.9  998.76   167.2  976.73
   196.7  967.48   216.4  964.28   324.6  936.02     364  929.46   432.8  926.29
   501.7  912.75     541  907.38   696.9  898.43   774.6  890.81  1038.7  892.06
  1053.7  894.61  1104.3  917.95  1123.7  930.04  1152.7  935.77  1191.4  953.65
  1230.1  989.71  1249.5 1021.28  1259.1 1031.67  1307.5 1046.24  1326.9  1049.7
    1414 1075.93  1433.3 1083.54  1452.7 1087.76  1491.4 1101.32  1501.1 1102.45
#Mann= 3 , 0 , 0
       0      .1       0  1038.7    .045       0  1053.7      .1       0
Bank Sta=1038.7,1053.7
XS Rating Curve= 0 ,0
Exp/Cntr=0.3,0.1

Type RM Length L Ch R = 1 ,48560.6 ,476.962,485.745,494.406
XS GIS Cut Line= 4
      1796291.94      331272.327     1796456.601       331802.81
     1796590.973      332235.709      1796740.79      332675.683
#Sta/Elev= 30
       0 1028.87    29.2 1015.47    68.2 1002.47   204.6     969   233.9  958.49
   321.6  936.33   360.6  931.45     458  928.04   584.4  917.04     623  910.66
   709.8  889.75     729  888.47  1008.4  890.79  1023.4  891.14  1086.2  894.41
  1105.6  897.71  1115.2  902.71  1144.3  925.15  1163.7   931.5  1192.7   946.9
  1231.4  989.81  1241.1  995.45  1260.5 1015.07  1270.2 1019.81  1299.2 1041.67
  1318.6 1049.82  1386.4 1090.71    1396 1093.21  1425.1 1108.59  1473.5 1123.61
#Mann= 3 , 0 , 0
       0      .1       0  1008.4    .045       0  1023.4      .1       0
Bank Sta=1008.4,1023.4
XS Rating Curve= 0 ,0
Exp/Cntr=0.3,0.1

Type RM Length L Ch R = 1 ,48074.9 ,392.528,400,407.436
XS GIS Cut Line= 4
     1796219.316      331303.733     1796174.671      331890.488
     1796139.933      332347.037     1796116.944      332801.571
#Sta/Elev= 30
       0 1029.16    19.6 1022.49    39.2 1009.56      49 1007.07    78.5  991.96
   117.7  980.15   166.7  970.47   274.6  938.34   343.3   929.7   441.3  927.26
     559  918.98   666.4  889.89   695.6  888.37  1038.8  888.91  1053.8  889.22
  1075.4  889.65  1114.1  905.27  1143.2  922.92  1230.3  946.54    1269  960.68
  1307.8  978.75  1336.8  998.76  1346.5 1002.92  1365.9 1017.99  1394.9 1034.13
  1433.7 1065.07  1443.3 1076.05  1462.7  1089.3  1491.8 1123.03  1501.4 1130.06
#Mann= 3 , 0 , 0
       0      .1       0  1038.8    .045       0  1053.8      .1       0
Bank Sta=1038.8,1053.8
XS Rating Curve= 0 ,0
Exp/Cntr=0.3,0.1

Type RM Length L Ch R = 1 ,47674.9 ,504.395,512.808,521.831
XS GIS Cut Line= 4
     1796162.303      331307.412     1795933.341      331845.029
     1795755.404      332262.835      1795585.98      332692.524
#Sta/Elev= 30
       0 1041.86    19.5 1036.38    48.7 1019.97    77.9  997.85   116.9  980.39
   175.3  966.26   253.2  937.85   506.4   919.2     623  914.99   709.9  887.55
   796.9  885.17    1031   887.3    1046  891.63  1087.6  908.62  1107.3  920.51
  1136.7  927.94  1166.2  940.64  1185.9  955.27  1254.7  995.83  1274.3 1011.65
  1284.1 1014.56  1323.5 1040.72  1333.3 1049.85  1362.8 1088.27  1372.6 1093.93
  1392.2 1118.84  1411.9  1136.7  1441.4 1181.78  1470.9  1209.4  1500.3 1219.37
#Mann= 3 , 0 , 0
       0      .1       0    1031    .045       0    1046      .1       0
Bank Sta=1031,1046
XS Rating Curve= 0 ,0
Exp/Cntr=0.3,0.1