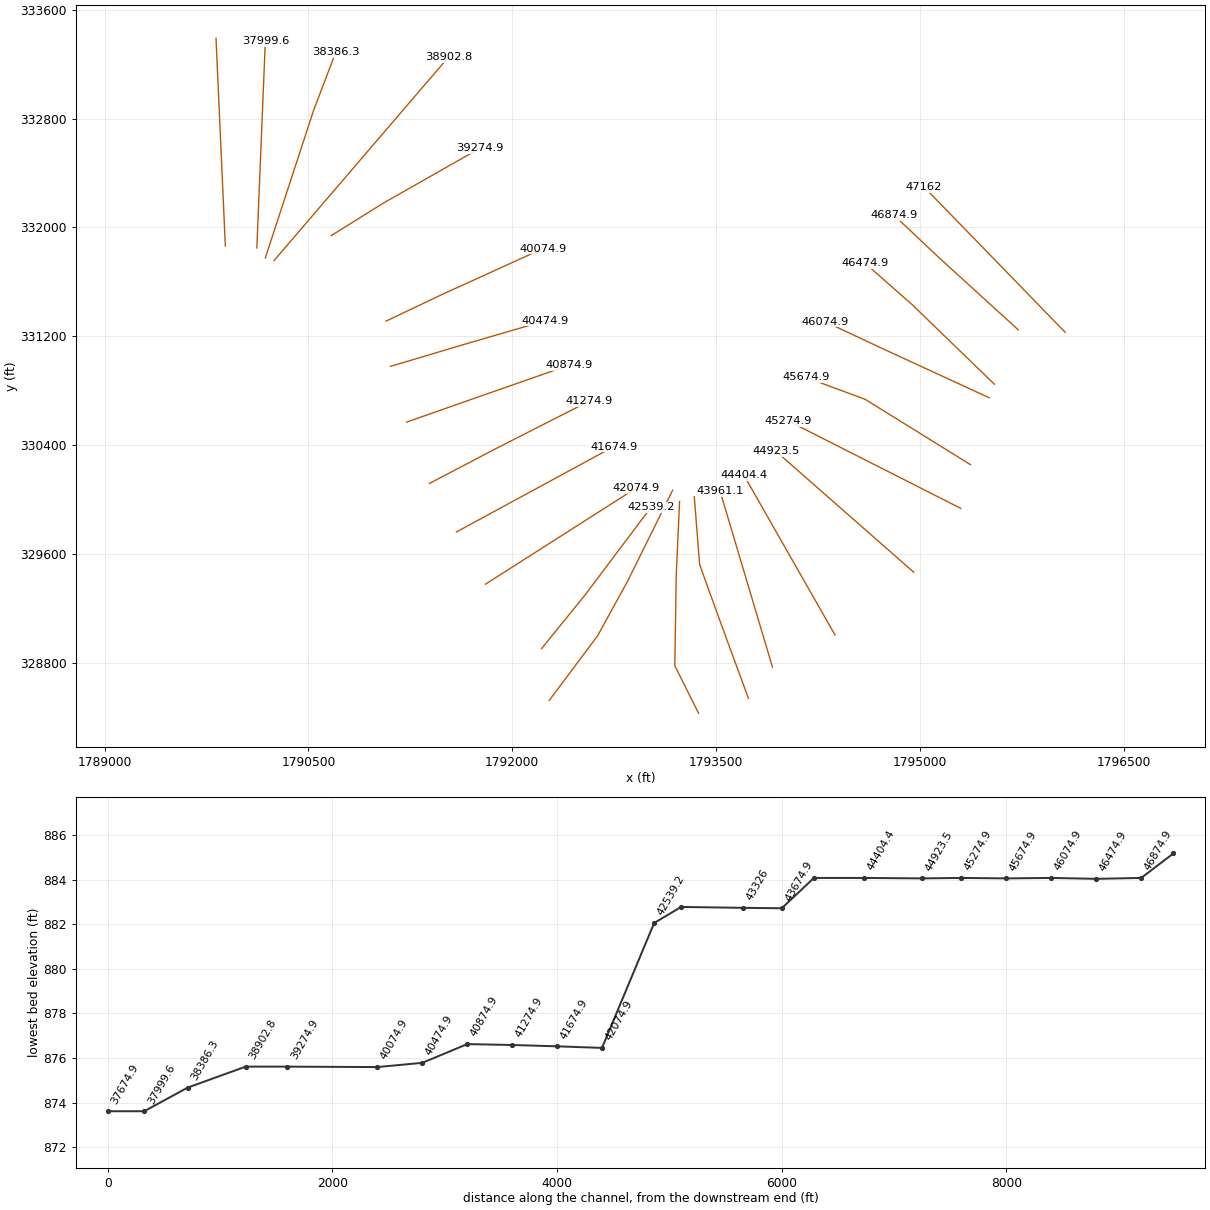
HEC-RAS study TygrtVlyRv.prj: TygrtVlyRv

--- TygrtVlyRv.g01 (geometry) --- (continued)

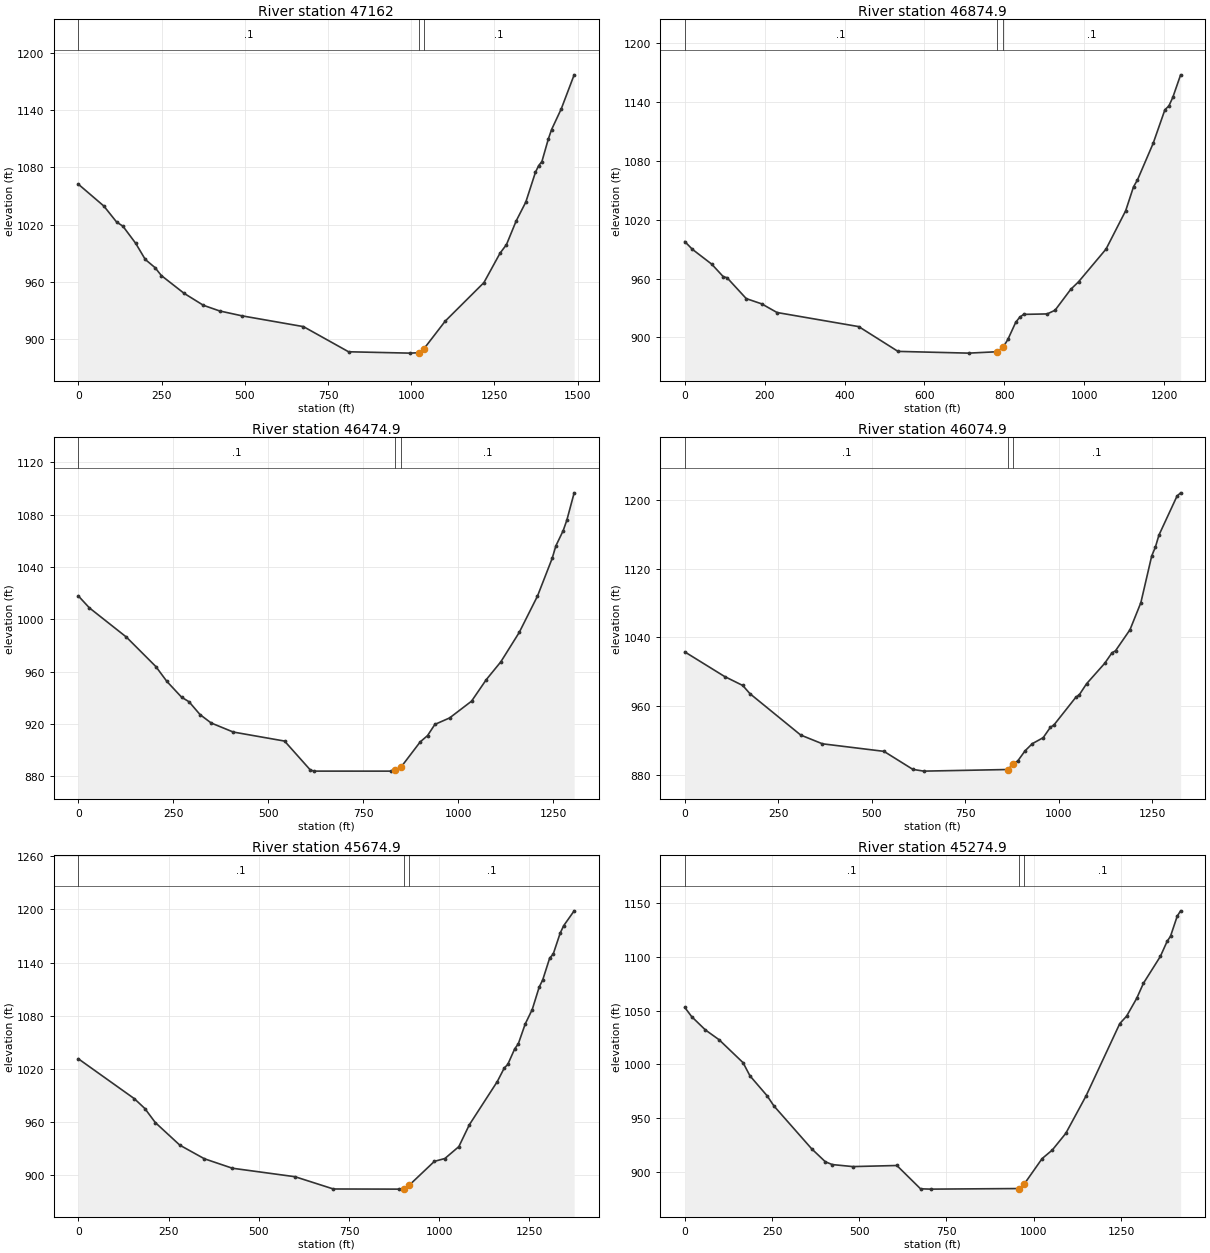
Type RM Length L Ch R = 1 ,47162   ,285.893,287.192,288.079
XS GIS Cut Line= 5
     1796069.481      331228.613     1795936.027      331365.878
     1795665.554      331644.077     1795348.382      331970.308
      1795031.21       332296.54
#Sta/Elev= 30
       0  1062.3    76.6 1039.41   114.9 1022.66     134 1018.24   172.3 1000.31
   201.1  983.39   230.2  974.89   249.6  966.46   317.5  947.92   375.7  935.32
   424.3  929.41   492.2  924.23   676.3  912.96   811.8  886.59   995.7  885.17
  1023.1  885.59  1038.1  889.68  1102.2  918.74  1218.4  959.11  1266.8  989.94
  1286.2  998.99  1315.2 1023.69  1344.2 1043.52  1373.3  1074.9    1383 1081.84
  1392.6 1086.04    1412 1109.78  1421.7 1119.59  1450.7 1141.25  1489.5 1176.97
#Mann= 3 , 0 , 0
       0      .1       0  1023.1    .045       0  1038.1      .1       0
Bank Sta=1023.1,1038.1
XS Rating Curve= 0 ,0
Exp/Cntr=0.3,0.1

Type RM Length L Ch R = 1 ,46874.9 ,400.614,400,400.856
XS GIS Cut Line= 4
     1795723.086      331247.831     1795488.212      331461.443
     1795139.247      331778.819     1794810.441      332089.041
#Sta/Elev= 30
       0   997.6    19.2  989.66    67.3  974.66    96.2  961.94   105.8  960.79
   153.9  939.54   192.4  934.23   230.9  925.41   435.4  911.06   533.7  885.84
   710.6  884.07   781.7  885.48   796.7  889.97   808.8  898.04   828.5  915.52
   838.3  920.55   848.2   923.5   907.1  923.98   926.8  927.68   966.1  948.99
   985.7  956.67  1054.5  989.98  1103.7 1029.04  1123.3 1053.39  1133.1 1060.28
  1172.4 1097.55  1201.9 1131.81  1211.8 1135.64  1221.6 1144.37  1241.2 1167.32
#Mann= 3 , 0 , 0
       0      .1       0   781.7    .045       0   796.7      .1       0
Bank Sta=781.7,796.7
XS Rating Curve= 0 ,0
Exp/Cntr=0.3,0.1

Type RM Length L Ch R = 1 ,46474.9 ,392.368,400,406.413
XS GIS Cut Line= 4
     1795548.013      330847.553     1795268.586      331117.484
     1794942.372      331432.611     1794594.521      331738.382
#Sta/Elev= 30
       0 1017.92    29.1 1008.78   126.3  986.51     204  963.96   233.1  952.58
     272  940.48   291.4  937.05   320.5   927.2   349.7  920.81   407.8   913.9
   542.9     907   610.5  884.96   620.1  884.04   822.8  884.03   834.6  884.53
   849.6  887.17     900  906.38   919.3   911.2   938.6  919.74   977.2  924.66
  1035.1  937.49  1073.6  953.84  1112.2  967.57  1160.5  989.97  1208.7 1017.82
  1247.3 1046.59    1257  1056.1  1276.3  1067.8  1285.9 1075.75  1305.2 1096.69
#Mann= 3 , 0 , 0
       0      .1       0   834.6    .045       0   849.6      .1       0
Bank Sta=834.6,849.6
XS Rating Curve= 0 ,0
Exp/Cntr=0.3,0.1

Type RM Length L Ch R = 1 ,46074.9 ,402.859,400,401.875
XS GIS Cut Line= 4
       1795509.1      330747.837     1795130.647      330922.063
     1794717.328      331112.339     1794305.393      331305.555
#Sta/Elev= 30
       0 1022.98   106.6  994.29     155  983.88   174.4  974.28   310.1  926.11
   368.2  915.91   532.8  907.12   610.3  886.08   639.3  884.07   864.1  885.94
   879.1   892.7     891  896.03   910.4  907.73   929.7  916.05   958.8  923.01
   978.1   935.1   987.8  937.94  1045.9  969.95  1055.6  973.12  1074.9  985.85
  1123.3 1009.59  1142.7 1021.78  1152.4 1024.32  1191.1  1048.8  1220.2 1080.35
  1249.2 1134.76  1258.9 1144.86  1268.6 1159.08    1317 1204.56  1326.6 1208.32
#Mann= 3 , 0 , 0
       0      .1       0   864.1    .045       0   879.1      .1       0
Bank Sta=864.1,879.1
XS Rating Curve= 0 ,0
Exp/Cntr=0.3,0.1

Type RM Length L Ch R = 1 ,45674.9 ,398.064,400,397.363
XS GIS Cut Line= 4
     1795371.812       330255.69     1794984.406      330496.024
     1794599.216      330734.985     1794163.468      330896.387
#Sta/Elev= 30
       0 1031.27   155.2  986.21   184.3  975.11   213.4  959.19   281.3   933.7
   349.2  918.36   426.8  907.66   600.6  898.05   706.7  884.21   889.9  884.05
   901.7   884.5   916.7  888.42   986.6  915.42  1015.7  918.63  1054.4  932.08
  1083.4   956.7  1160.9 1005.54  1180.3 1020.92  1189.9 1024.86  1209.3 1042.61
    1219    1048  1238.3 1070.63  1257.7 1086.89  1277.1 1112.38  1286.7 1120.26
  1306.1 1145.06  1315.8 1149.46  1335.1 1173.12  1344.8 1181.55  1373.9 1198.38
#Mann= 3 , 0 , 0
       0      .1       0   901.7    .045       0   916.7      .1       0
Bank Sta=901.7,916.7
XS Rating Curve= 0 ,0
Exp/Cntr=0.3,0.1

Type RM Length L Ch R = 1 ,45274.9 ,357.043,351.313,345.583
XS GIS Cut Line= 4
     1795301.059      329934.087     1794845.212       330165.01
     1794439.322      330370.627     1794033.432      330576.243
#Sta/Elev= 30
       0 1052.94    19.7 1044.38      59 1032.02    98.3 1022.92   167.1 1001.56
   186.7  989.38   235.8  970.87   255.5  961.35   363.6  921.55   402.9  909.46
   422.6   906.9   481.5  905.02   607.8  906.03   675.6  884.37   704.6  884.07
   958.5  884.61   973.5  889.14  1024.1  912.48  1053.1  920.37  1091.9  935.91
  1149.9  970.67  1246.7 1037.97  1266.1 1044.81  1295.1 1061.38  1314.5 1075.46
  1362.9 1100.34  1382.3 1114.37    1392 1119.08  1411.3 1137.83    1421 1142.72
#Mann= 3 , 0 , 0
       0      .1       0   958.5    .045       0   973.5      .1       0
Bank Sta=958.5,973.5
XS Rating Curve= 0 ,0
Exp/Cntr=0.3,0.1

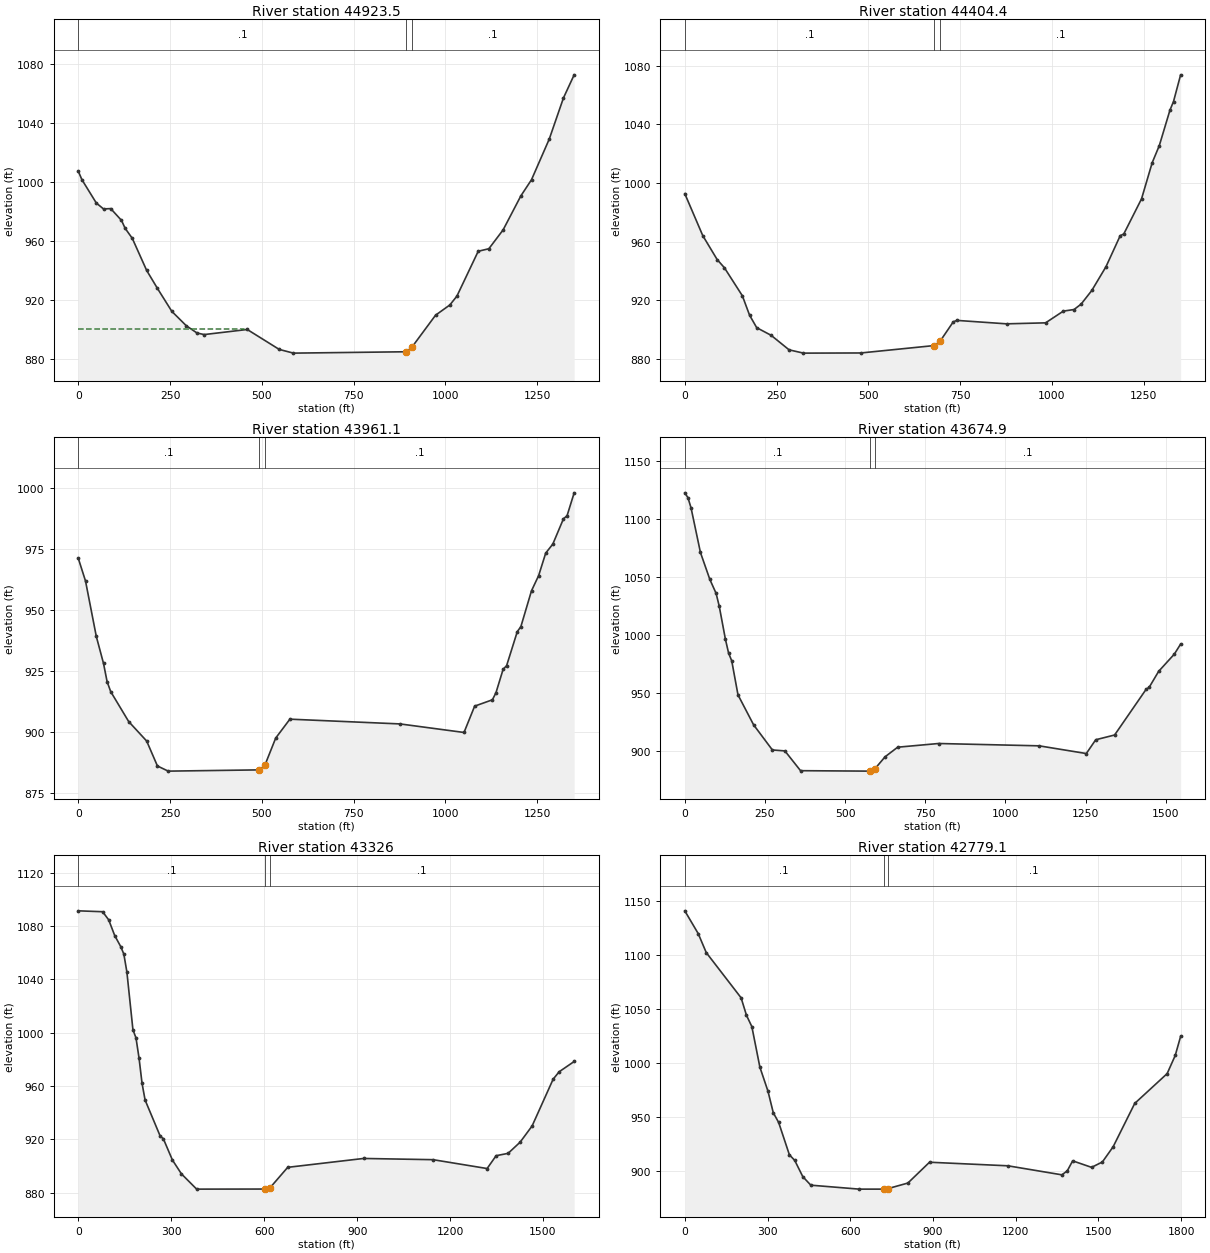
Type RM Length L Ch R = 1 ,44923.5 ,528.281,519.19,510.099
XS GIS Cut Line= 4
     1794954.465      329464.826     1794623.026      329755.563
     1794280.976      330055.608     1793938.926      330355.653
#Sta/Elev= 30
       0 1007.37     9.8 1001.72      49  985.89    68.6  981.88    88.2  982.11
   117.6  974.11   127.4  968.78     147  961.93   186.2  940.15   215.5  927.98
   254.7   912.4   293.9  902.69   323.3  897.71   342.9  896.64   460.2  900.09
   547.4  886.56   586.1  884.05   893.7  884.98   908.7  888.04   973.3  909.79
  1012.1  916.71  1031.4   922.7  1089.5  953.16  1118.5  954.88  1157.3  967.65
  1205.7  990.74  1234.7 1001.71  1283.1 1029.32  1321.8 1057.22  1350.9 1072.87
#Mann= 3 , 0 , 0
       0      .1       0   893.7    .045       0   908.7      .1       0
#XS Ineff= 2 , 0
          450.13  900.13
Permanent Ineff=
       F       F
Bank Sta=893.7,908.7
XS Rating Curve= 0 ,0
Exp/Cntr=0.3,0.1

Type RM Length L Ch R = 1 ,44404.4 ,447.715,443.21,438.522
XS GIS Cut Line= 4
     1794375.655      329003.179     1794157.068      329386.062
     1793931.484      329781.203     1793705.899      330176.344
#Sta/Elev= 30
       0  992.83      49  964.19    88.2  947.87   107.8  942.34   156.8   923.2
   176.4  909.99   195.9  901.42   235.1  896.24   284.1  886.32   323.3  884.07
   479.6  884.18   680.3  889.25   695.3  892.09   731.3  905.35     741   906.4
   876.5  904.05     983  904.72  1031.4  912.73  1060.5   913.8  1079.8  917.51
  1108.9   926.8  1147.6  943.04  1186.3  964.17    1196  965.33  1244.4  989.29
  1273.4 1013.91  1292.8  1025.6  1321.8 1049.77  1331.5 1055.66  1350.9 1073.87
#Mann= 3 , 0 , 0
       0      .1       0   680.3    .045       0   695.3      .1       0
Bank Sta=680.3,695.3
XS Rating Curve= 0 ,0
Exp/Cntr=0.3,0.1

Type RM Length L Ch R = 1 ,43961.1 ,283.885,286.287,288.727
XS GIS Cut Line= 4
     1793915.118      328767.234     1793789.183       329189.75
     1793659.216      329625.793     1793529.248      330061.836
#Sta/Elev= 30
       0  971.21    19.6  961.95      49  939.24    68.6   928.2    78.4  920.73
    88.2  916.65   137.2  904.38   186.2   896.4   215.5  886.18   244.9  884.07
     493  884.58     508  886.39   537.7   897.6   576.4  905.36   876.5  903.41
  1050.8  899.91  1079.8   910.7  1128.2   913.3  1137.9  916.21  1157.3  925.77
  1166.9   927.3    1196  941.25  1205.7  943.27  1234.7  957.98  1254.1  964.17
  1273.4  973.41  1292.8  977.11  1321.8  987.48  1331.5  988.69  1350.9   998.1
#Mann= 3 , 0 , 0
       0      .1       0     493    .045       0     508      .1       0
Bank Sta=493,508
XS Rating Curve= 0 ,0
Exp/Cntr=0.3,0.1

Type RM Length L Ch R = 1 ,43674.9 ,357.25,348.885,340.665
XS GIS Cut Line= 4
     1793738.113      328538.403     1793535.797      329087.779
      1793379.19      329521.321     1793339.871      330019.863
#Sta/Elev= 30
       0 1122.68     9.8 1118.52    19.5 1109.69    48.8 1071.23    78.1 1048.02
    97.6 1036.01   107.3 1025.05   126.8  996.27   136.6   984.5   146.4  977.79
   165.9  948.46   214.7  922.59   273.2  900.95   312.2  900.14     361  883.09
   575.7  882.71   577.9  882.96   592.9  884.69   624.7  895.07   663.9  903.34
   791.4  906.53  1105.2  904.52  1252.3  897.88  1281.7  909.76  1340.6  913.86
  1438.6  953.15  1448.4  954.97  1477.9  968.73  1526.9  983.61  1546.5  992.26
#Mann= 3 , 0 , 0
       0      .1       0   577.9    .045       0   592.9      .1       0
Bank Sta=577.9,592.9
XS Rating Curve= 0 ,0
Exp/Cntr=0.3,0.1

Type RM Length L Ch R = 1 ,43326   ,557.719,546.861,536.002
XS GIS Cut Line= 4
      1793371.73      328426.895     1793196.504      328777.348
     1793207.217      329443.451       1793231.6      329985.485
#Sta/Elev= 30
       0 1091.52    78.4 1090.85      98 1084.76   117.5 1072.93   137.1 1064.58
   146.9 1059.05   156.7 1045.69   176.3  1002.2   186.1  996.24   195.9  981.19
   205.7   962.1   215.5  949.58   264.5  922.38   274.3   920.6   303.7  904.57
     333  894.13     382  882.73     603  882.79     618  883.52   675.9  899.08
   920.9  905.74  1145.2  904.82  1319.6  898.18  1348.7   907.8  1387.4  909.58
  1426.2  917.97  1464.9  930.14  1532.8  965.24  1552.1  970.76  1600.6  978.49
#Mann= 3 , 0 , 0
       0      .1       0     603    .045       0     618      .1       0
Bank Sta=603,618
XS Rating Curve= 0 ,0
Exp/Cntr=0.3,0.1

Type RM Length L Ch R = 1 ,42779.1 ,243.846,239.921,236.469
XS GIS Cut Line= 4
     1792272.583      328522.473     1792628.253      328997.202
       1792850.4      329401.117     1793180.574      330067.652
#Sta/Elev= 30
       0  1140.7    48.6 1119.62    77.8 1101.99   204.2 1060.07   223.7 1043.83
   243.1 1033.43   272.3  995.79   301.5  973.62   320.9  953.53   340.4  944.54
   379.2  914.64   398.7  909.36   427.9  894.33     457  886.43   632.4  882.77
   720.7  882.77   735.7  883.18     809  888.41   887.4   907.7  1171.6  904.39
  1367.4  896.02  1386.9  899.68  1406.5  908.98    1475  902.96  1514.2  907.92
  1553.3  922.04  1631.6  962.21  1749.1  989.83  1778.4 1006.62    1798 1024.33
#Mann= 3 , 0 , 0
       0      .1       0   720.7    .045       0   735.7      .1       0
Bank Sta=720.7,735.7
XS Rating Curve= 0 ,0
Exp/Cntr=0.3,0.1

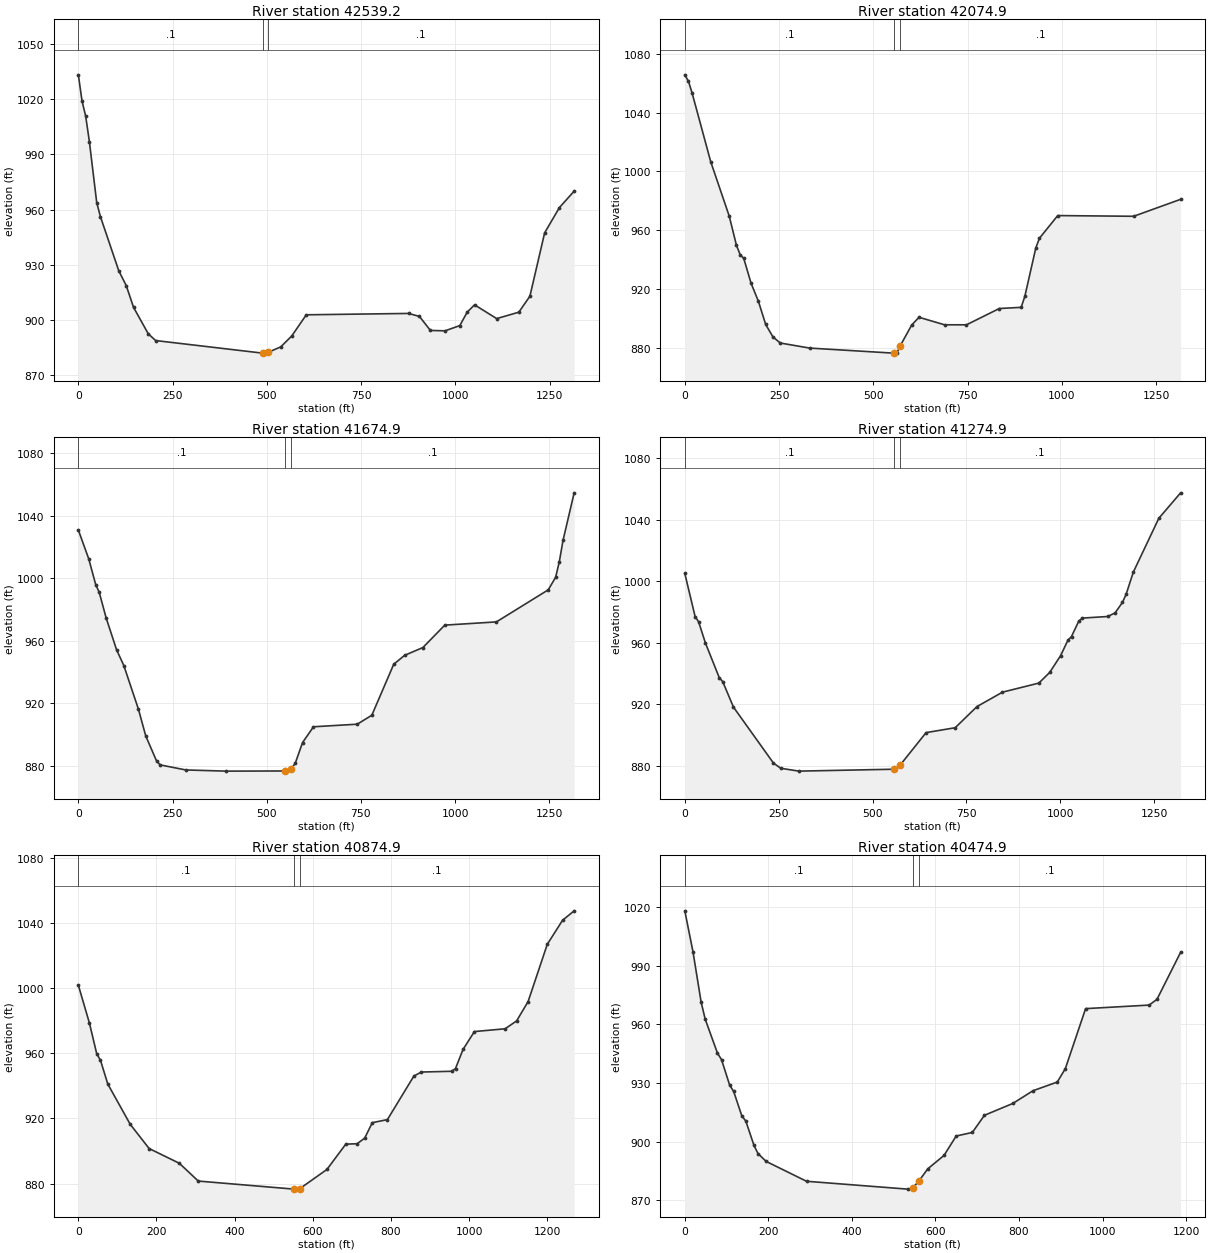
Type RM Length L Ch R = 1 ,42539.2 ,471.829,464.333,456.366
XS GIS Cut Line= 4
     1792216.025      328902.839     1792535.972       329297.33
     1792809.636      329660.831     1793021.515      329942.264
#Sta/Elev= 30
       0 1033.23     9.8 1019.05    19.5 1010.79    29.3  996.96    48.8  963.78
    58.6  956.19   107.4  926.72     127  918.78   146.5   906.9   185.6  892.52
   205.1  888.88   488.4  882.05     489  882.06     504  882.53     537  885.45
     566  891.35   604.7  902.87   875.8  903.61   904.8  901.99   933.9  894.38
   972.7  894.16  1011.9  897.01  1031.4  904.29    1051  908.29  1109.7  900.81
  1168.4  904.29  1197.8  912.96  1236.9  947.39  1276.1  961.12  1315.2  970.05
#Mann= 3 , 0 , 0
       0      .1       0     489    .045       0     504      .1       0
Bank Sta=489,504
XS Rating Curve= 0 ,0
Exp/Cntr=0.3,0.1

Type RM Length L Ch R = 1 ,42074.9 ,401.583,400,398.417
XS GIS Cut Line= 5
     1791803.443      329376.938     1791894.525      329434.963
      1792278.27      329679.431     1792662.015      329923.899
     1792912.403      330083.412
#Sta/Elev= 30
       0 1065.62     9.8 1061.17    19.6 1053.04    68.7 1006.59   117.7   969.7
     137  949.71   146.7  943.47   156.4  940.79   175.8  923.91   195.1  911.75
   214.5  895.95   233.8  887.46   253.2  883.33   330.7  879.89   553.3  876.45
   555.5  876.51     563  876.73   570.5  881.05   601.7  895.54   621.1  900.82
   688.8  895.71   746.9  895.69   834.1  906.78   892.1  907.57   901.8  915.09
   930.9  947.98   940.5  954.54     989  969.95  1190.4  969.47  1314.9     981
#Mann= 3 , 0 , 0
       0      .1       0   555.5    .045       0   570.5      .1       0
Bank Sta=555.5,570.5
XS Rating Curve= 0 ,0
Exp/Cntr=0.3,0.1

Type RM Length L Ch R = 1 ,41674.9 ,400.331,400,399.396
XS GIS Cut Line= 5
     1791589.545      329760.696     1791678.726      329809.055
     1792078.707      330025.943     1792478.687      330242.832
     1792746.507      330388.056
#Sta/Elev= 30
       0 1030.81    27.7 1012.29    46.1  995.88    55.3  991.03    73.8  974.57
   101.4  954.24   120.8  944.04   159.5  916.18   178.9  899.07   207.9  882.86
   217.6  880.48   285.4  877.27   391.9  876.52   548.9  876.62   563.9  877.61
   575.8  881.57   595.2  894.81   624.2   904.9   740.4  906.55   779.1   912.3
   837.2  944.92   866.2  950.62   914.6   955.6   972.7  969.94  1109.7     972
  1247.3  992.52    1267 1000.59  1276.8 1010.64  1286.6 1024.22  1316.1 1054.59
#Mann= 3 , 0 , 0
       0      .1       0   548.9    .045       0   563.9      .1       0
Bank Sta=548.9,563.9
XS Rating Curve= 0 ,0
Exp/Cntr=0.3,0.1

Type RM Length L Ch R = 1 ,41274.9 ,403.258,400,396.98
XS GIS Cut Line= 5
     1791390.757      330117.344     1791488.385       330168.44
     1791891.504      330379.422     1792297.196       330585.52
     1792564.916      330721.525
#Sta/Elev= 30
       0 1005.01    27.5  976.98    36.7  973.61    55.1   959.7    91.8   937.3
     101  934.72   129.6  918.17     236  881.84   255.4  878.44   303.8  876.58
   557.7  877.82   572.7  880.26   642.6   901.6   720.1  904.77   778.2  918.53
     846  927.87   942.8  933.76   971.8  940.68  1000.9  951.62  1020.2  961.56
  1029.9  964.03  1049.3  974.05    1059     976  1126.8  977.04  1146.2  979.44
  1165.5  986.17  1175.2  991.36  1194.6  1005.9  1262.4 1040.81  1320.5 1057.37
#Mann= 3 , 0 , 0
       0      .1       0   557.7    .045       0   572.7      .1       0
Bank Sta=557.7,572.7
XS Rating Curve= 0 ,0
Exp/Cntr=0.3,0.1

Type RM Length L Ch R = 1 ,40874.9 ,401.071,400,398.821
XS GIS Cut Line= 5
     1791222.323       330568.16     1791320.213      330602.507
     1791749.541      330753.145     1792179.151      330903.132
     1792420.194      330987.286
#Sta/Elev= 30
       0 1001.81    28.3  978.62    47.2  959.57    56.6  955.77    75.4  941.12
   132.8  916.42   181.2  901.54   258.6  892.48     307  881.57   551.2  876.64
   558.7  876.62   566.2   876.8   636.2  888.68   684.6  904.23   713.6  904.48
     733  907.92   752.4   917.4   791.1  919.29   858.9  946.04   878.2  948.49
   955.7  948.95   965.4  950.65   984.7  962.37  1013.8  973.33  1092.3  975.03
  1121.8  979.86  1151.2  991.73  1200.3 1026.89  1239.6 1041.68  1269.1 1047.43
#Mann= 3 , 0 , 0
       0      .1       0   551.2    .045       0   566.2      .1       0
Bank Sta=551.2,566.2
XS Rating Curve= 0 ,0
Exp/Cntr=0.3,0.1

Type RM Length L Ch R = 1 ,40474.9 ,396.543,400,403.227
XS GIS Cut Line= 5
     1791104.321      330978.061     1791197.893       331005.97
     1791633.922      331136.022     1792070.757      331263.296
     1792242.624       331313.37
#Sta/Elev= 30
       0 1018.03    19.5  997.22    39.1  971.36    48.8  962.67    78.1  945.34
    87.9  941.95   107.3  928.99     117  925.69   136.4  913.27   146.1  910.55
   165.4  898.24   175.1  893.98   194.5  889.97   291.3   879.8   533.3  875.78
   545.2  876.29   560.2  879.92   581.7  886.19   620.4     893   649.5  902.92
   688.2  904.76   717.2  913.53     785  919.56   833.4  926.08   891.5  930.51
   910.8  937.39   959.3  968.04  1111.3  969.85  1130.1  972.79  1186.7  996.84
#Mann= 3 , 0 , 0
       0      .1       0   545.2    .045       0   560.2      .1       0
Bank Sta=545.2,560.2
XS Rating Curve= 0 ,0
Exp/Cntr=0.3,0.1

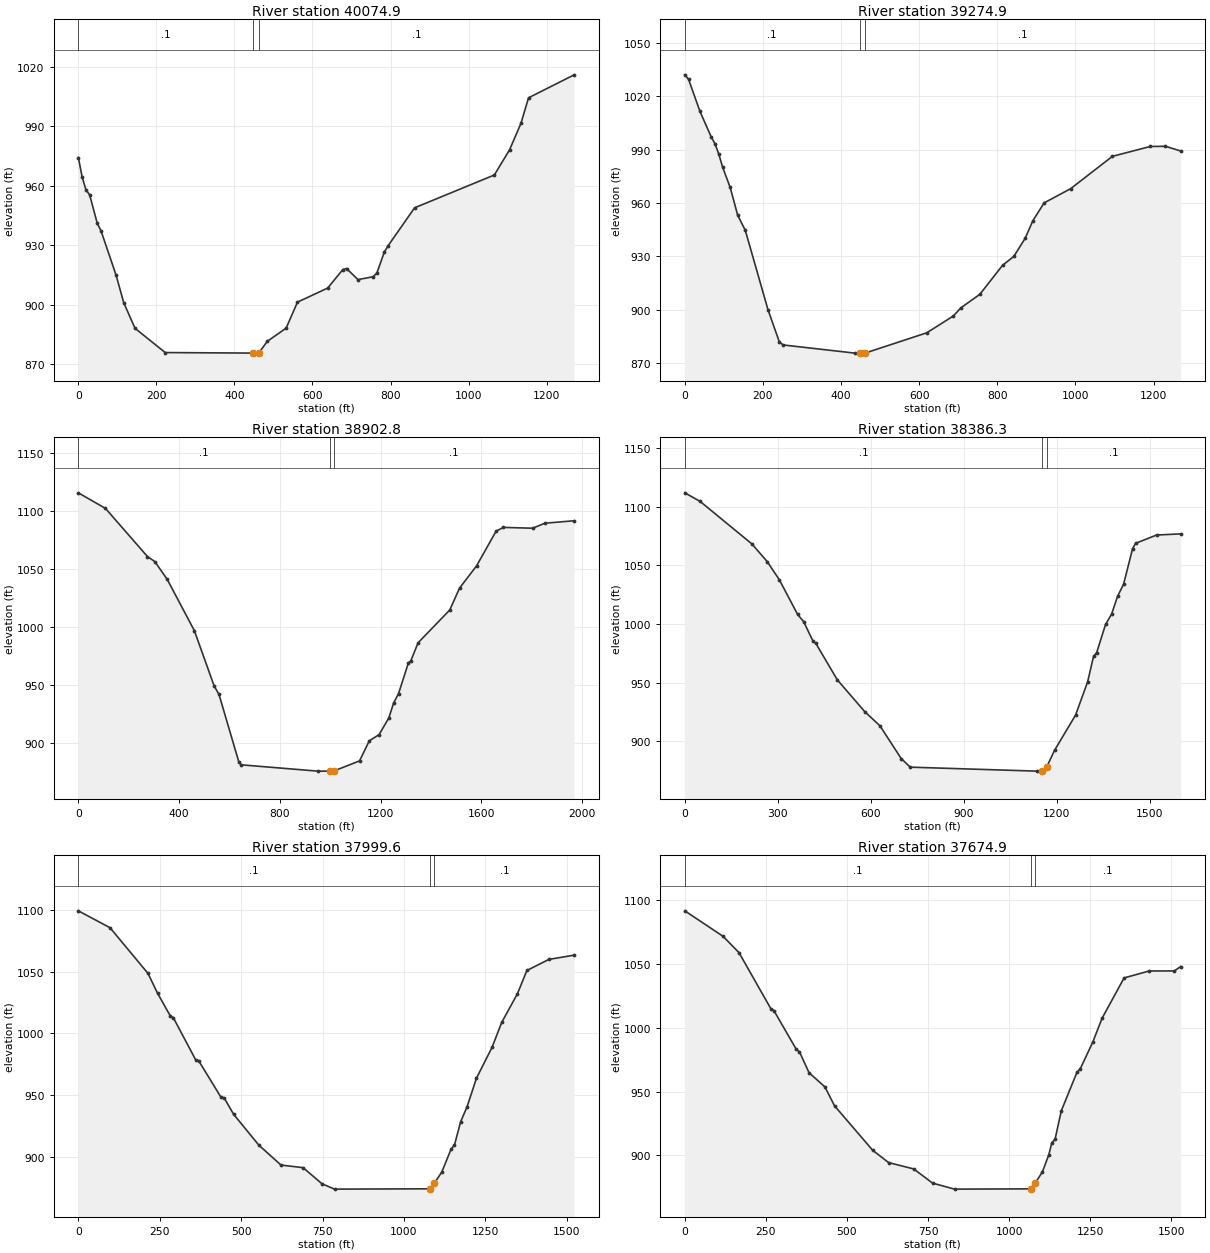
Type RM Length L Ch R = 1 ,40074.9 ,797.448,800,802.013
XS GIS Cut Line= 4
     1791071.742      331310.932     1791482.805      331506.178
     1791896.964      331694.552     1792225.195      331843.842
#Sta/Elev= 30
       0  974.17     9.7  964.45    19.4   957.9      29  955.36    48.4  941.05
    58.1  937.24    96.8  914.85   116.2  901.09   145.2  888.11   222.7  875.87
   447.6  875.61   455.1  875.59   462.6  875.69   484.1  881.51   532.5  888.18
   561.6  901.29     639  908.39   677.7  917.67   687.4  918.22   716.5  912.65
   755.2  914.07   764.9  915.87   784.2  926.54   793.9  929.73   861.7  948.82
    1066  965.36    1105  978.01  1134.2  991.36  1153.7 1004.27  1270.6 1015.84
#Mann= 3 , 0 , 0
       0      .1       0   447.6    .045       0   462.6      .1       0
Bank Sta=447.6,462.6
XS Rating Curve= 0 ,0
Exp/Cntr=0.3,0.1

Type RM Length L Ch R = 1 ,39274.9 ,364.711,372.057,380.313
XS GIS Cut Line= 4
     1790667.032      331938.959     1791053.246      332179.357
     1791449.336       332404.19     1791761.572      332581.424
#Sta/Elev= 30
       0 1032.18     9.7 1029.63    38.7 1011.68    67.8  997.14    77.4  993.34
    87.1  987.49    96.8  980.26   116.1  968.87   135.5  953.14   154.9  944.68
   212.9  900.08     242  881.92   251.7  880.21   435.6  875.61   447.4  875.62
   462.4  875.69   619.7  887.06   687.5   896.5   706.9  901.11   755.3  908.67
   813.5  925.01   842.5  930.05   871.6  940.29     891  950.07   920.1  960.16
     988  968.15  1094.7  986.32  1191.8  991.87  1230.6  991.97  1269.4  989.35
#Mann= 3 , 0 , 0
       0      .1       0   447.4    .045       0   462.4      .1       0
Bank Sta=447.4,462.4
XS Rating Curve= 0 ,0
Exp/Cntr=0.3,0.1

Type RM Length L Ch R = 1 ,38902.8 ,508.806,516.497,523.833
XS GIS Cut Line= 4
     1790246.908       331755.62     1790936.046      332558.762
     1791232.337      332904.069     1791528.996      333249.059
#Sta/Elev= 30
       0 1115.68   107.8 1102.23   274.4 1060.72   303.8 1056.34   352.8 1041.04
   460.5  996.82   538.9  949.22   558.5  941.72   636.9  883.69   646.7  881.05
   950.5  875.61   998.3  875.61  1013.3  875.63  1116.4  884.46  1155.1  901.79
  1193.8  907.07  1232.5  921.47  1251.9  934.47  1271.3  942.57    1310  968.79
  1319.7  970.65  1348.7  986.32  1474.6 1014.66  1513.3 1033.47    1581 1052.73
  1658.5 1082.64  1687.5 1085.86  1803.7 1085.15  1852.1 1089.47  1968.3 1091.59
#Mann= 3 , 0 , 0
       0      .1       0   998.3    .045       0  1013.3      .1       0
Bank Sta=998.3,1013.3
XS Rating Curve= 0 ,0
Exp/Cntr=0.3,0.1

Type RM Length L Ch R = 1 ,38386.3 ,379.714,386.686,394.01
XS GIS Cut Line= 4
     1790183.039       331775.43     1790397.238      332429.596
     1790539.029      332862.627     1790701.435      333287.532
#Sta/Elev= 30
       0 1111.78    49.2 1104.51   216.3 1068.27   265.5 1053.27   304.8 1037.75
   363.8 1008.19   383.5 1001.91     413  985.63   422.8  983.41   491.7  952.48
   580.2  925.39   629.3   913.3     698  885.32   727.1  878.05  1134.3  874.67
  1151.8  874.94  1166.8  878.07  1192.4  892.43  1260.1  922.41  1298.9  950.64
  1318.2  972.54  1327.9  975.43  1356.9  999.66  1376.3 1008.42  1395.6 1023.63
    1415 1033.97    1444 1064.21  1453.7 1068.77  1521.5 1075.83  1598.9  1076.8
#Mann= 3 , 0 , 0
       0      .1       0  1151.8    .045       0  1166.8      .1       0
Bank Sta=1151.8,1166.8
XS Rating Curve= 0 ,0
Exp/Cntr=0.3,0.1

Type RM Length L Ch R = 1 ,37999.6 ,322.824,324.761,326.698
XS GIS Cut Line= 4
     1790120.623      331848.902     1790145.802      332461.221
     1790164.496      332915.836      1790183.19      333370.452
#Sta/Elev= 30
       0 1099.46    97.3 1085.76     214 1048.65   243.2 1032.64   282.1 1014.35
   291.8 1012.71   359.9  978.79   369.6   977.8   437.7  948.34   447.5  947.81
   476.7  934.42   554.5  909.27   622.5  893.13   690.3  891.04   748.4  877.92
   787.1  873.61  1078.6  873.87  1093.6  878.52  1116.2   887.4  1145.3  906.38
    1155  909.17  1174.3  928.42  1193.7  940.27  1222.7  963.59  1271.1  988.95
  1300.2 1008.86  1348.6 1032.17  1377.6 1051.04  1445.4 1060.06  1522.8 1063.48
#Mann= 3 , 0 , 0
       0      .1       0  1078.6    .045       0  1093.6      .1       0
Bank Sta=1078.6,1093.6
XS Rating Curve= 0 ,0
Exp/Cntr=0.3,0.1

Type RM Length L Ch R = 1 ,37674.9 ,398.295,400,401.705
XS GIS Cut Line= 4
     1789888.887      331862.683     1789861.074      332480.814
     1789840.622      332935.354     1789820.169      333389.894
#Sta/Elev= 30
       0 1091.74   117.9 1071.78     167 1059.01   265.2 1015.09     275 1013.45
   343.8  983.16   353.6  981.26     383  964.89   432.1  953.73   461.6  938.93
   579.5  904.02   628.4  894.41   705.9  889.43     764  878.32   831.7  873.61
  1066.3  873.82  1081.3  878.64  1102.8  887.18  1122.2  900.43  1131.8  910.04
  1141.5  912.52  1160.9  935.01  1209.3  965.24    1219  967.74  1257.7  988.68
  1286.7  1007.6  1354.5 1039.15  1431.9  1044.6  1509.4 1044.62  1528.8 1048.04
#Mann= 3 , 0 , 0
       0      .1       0  1066.3    .045       0  1081.3      .1       0
Bank Sta=1066.3,1081.3
XS Rating Curve= 0 ,0
Exp/Cntr=0.3,0.1