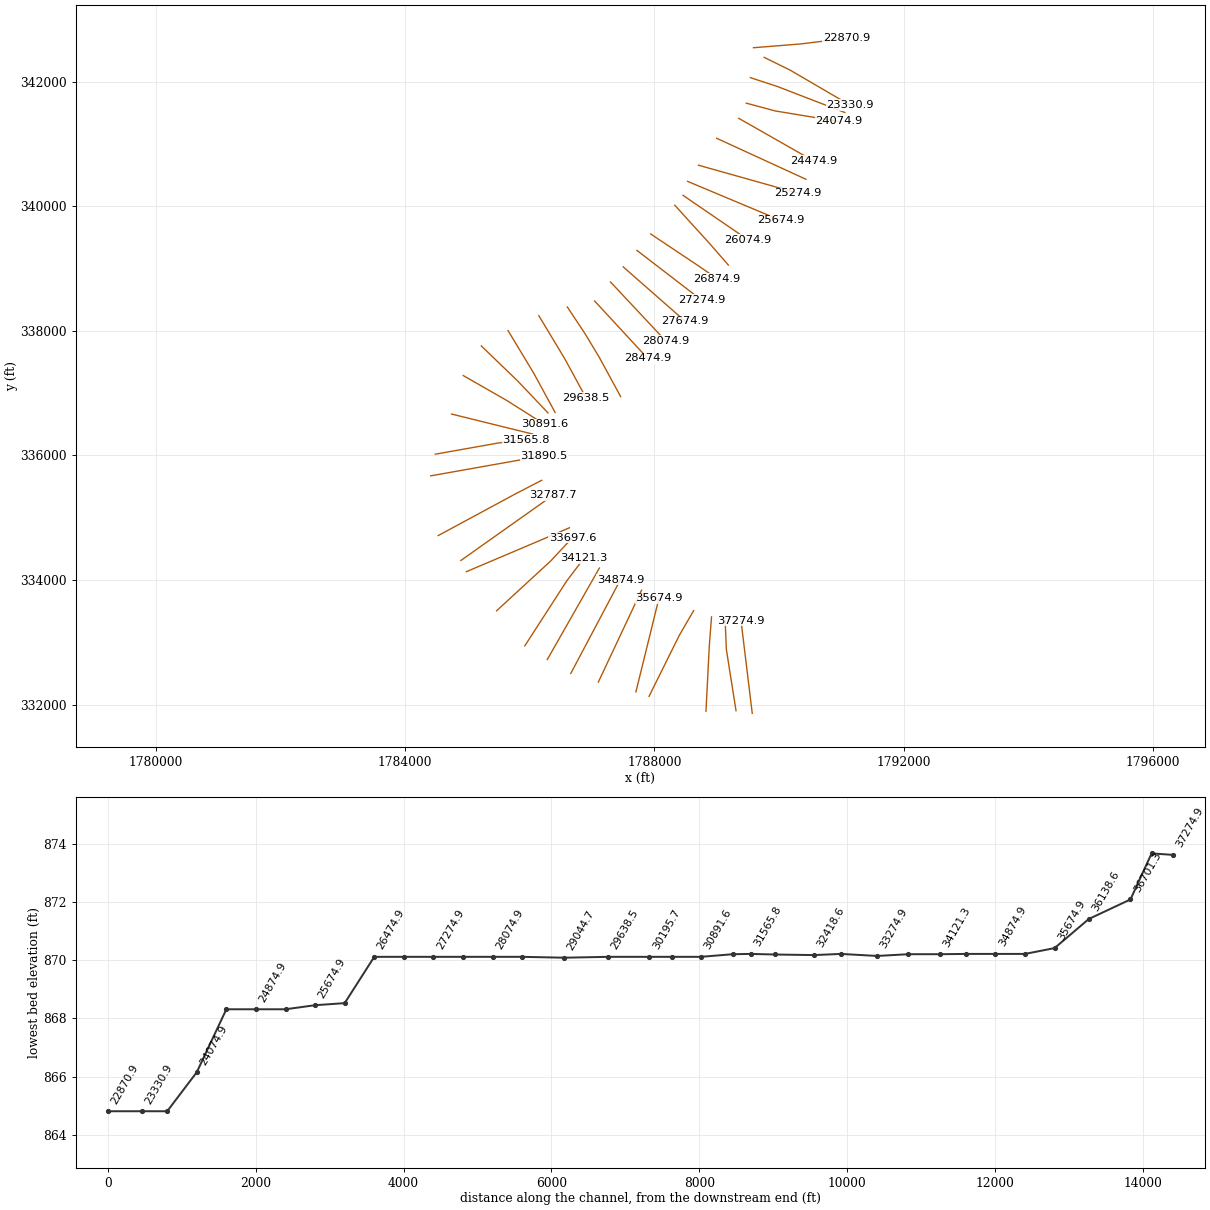
HEC-RAS study TygrtVlyRv.prj: TygrtVlyRv

--- TygrtVlyRv.g01 (geometry) --- (continued)

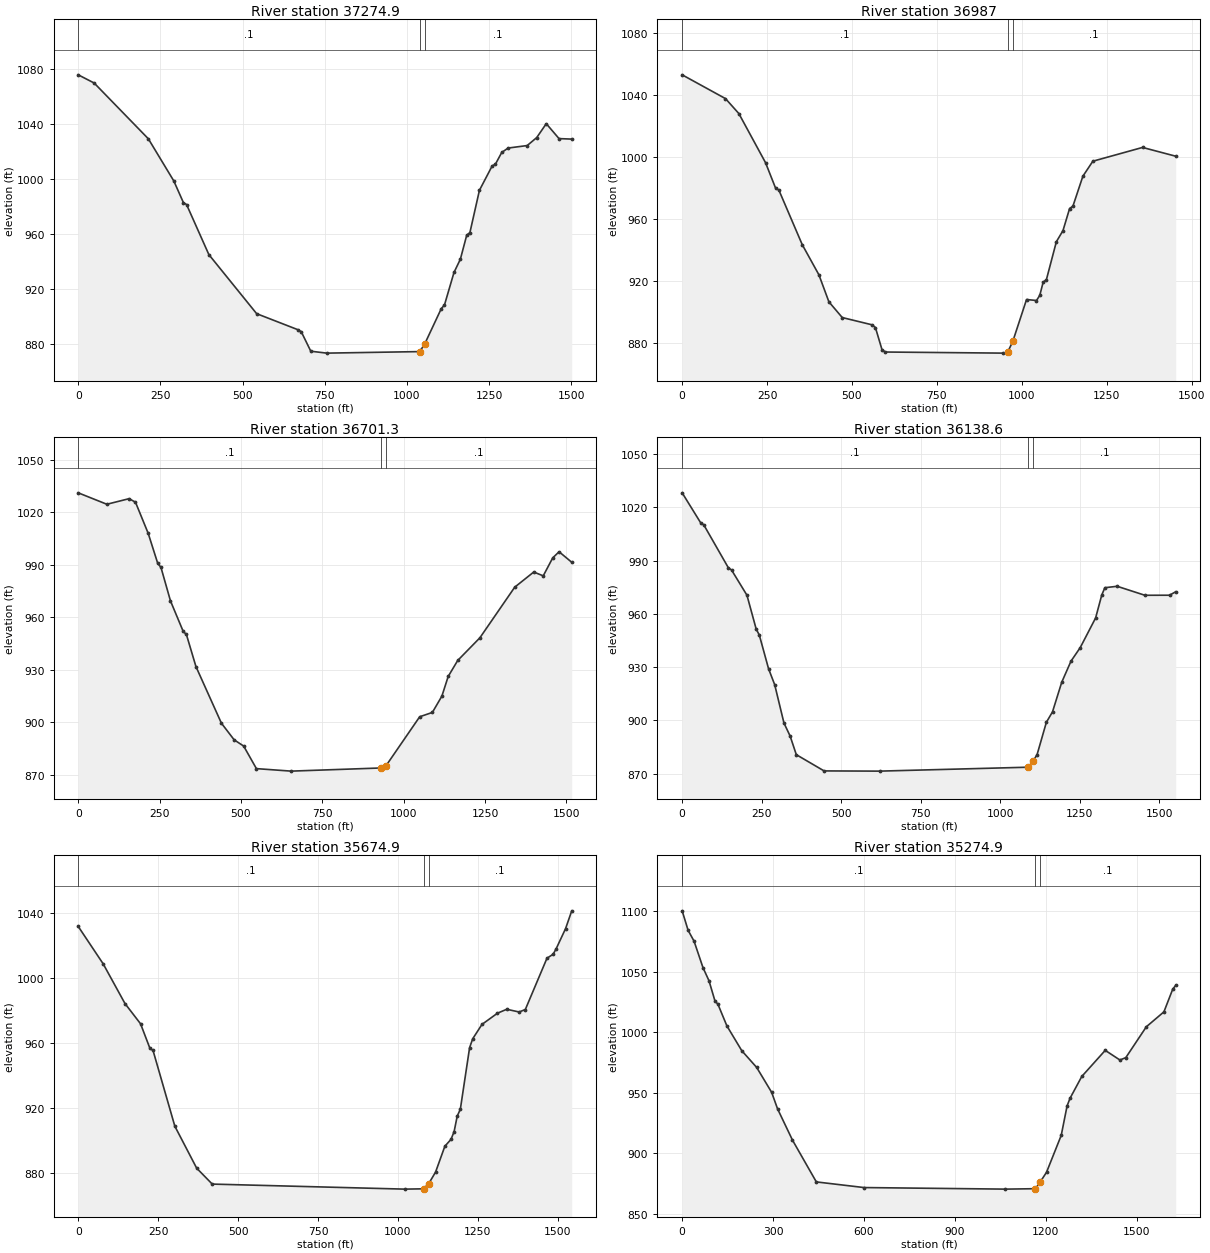
Type RM Length L Ch R = 1 ,37274.9 ,287.101,287.904,288.707
XS GIS Cut Line= 4
     1789568.528       331861.22      1789497.34      332448.206
     1789442.561      332899.897     1789387.781      333351.587
#Sta/Elev= 30
       0 1075.68    48.5 1069.73   213.3 1029.24   290.8  998.62   319.9  982.95
   329.6  981.49   397.4  945.16   542.8  902.25   668.7  890.58   678.4  889.19
   707.5     875   755.9  873.61  1038.8  874.72  1053.8  880.15  1104.4  905.91
  1114.1  908.54  1143.1  932.18  1162.5  941.82  1181.8  959.23  1191.5  961.14
  1220.5  991.85  1259.3 1009.57  1268.9 1010.71  1288.3  1019.3  1307.7 1022.51
  1365.8 1024.33  1394.8 1030.12  1423.8 1040.21  1462.6 1029.37  1501.3 1029.01
#Mann= 3 , 0 , 0
       0      .1       0  1038.8    .045       0  1053.8      .1       0
Bank Sta=1038.8,1053.8
XS Rating Curve= 0 ,0
Exp/Cntr=0.3,0.1

Type RM Length L Ch R = 1 ,36987   ,290.294,285.611,281.638
XS GIS Cut Line= 4
     1789308.033      331905.101     1789223.924      332438.522
     1789153.158      332887.329     1789134.168      333345.608
#Sta/Elev= 30
       0 1052.77   127.6 1037.46   166.9 1027.85   245.5  996.22   274.9  979.93
   284.7  978.61   353.5  943.49   402.6  924.07     432  906.69   471.3  896.56
   559.3  891.87     569  890.12   588.3  875.93     598  874.37     946  873.66
   958.4  874.37   973.4  881.19  1013.9  908.16  1043.2  907.53  1052.9  910.84
  1062.7  919.23  1072.4  920.98  1101.7  945.36  1121.2  952.52  1140.7  966.74
  1150.5  968.28  1179.8  987.53  1209.1  997.17  1355.4 1006.04    1453  1000.4
#Mann= 3 , 0 , 0
       0      .1       0   958.4    .045       0   973.4      .1       0
Bank Sta=958.4,973.4
XS Rating Curve= 0 ,0
Exp/Cntr=0.3,0.1

Type RM Length L Ch R = 1 ,36701.3 ,572.038,562.711,551.261
XS GIS Cut Line= 4
      1788826.14      331896.767     1788856.622      332492.377
     1788879.768      332944.643     1788915.179      333410.437
#Sta/Elev= 30
       0 1031.22      88 1024.68   156.4 1027.88     176 1025.84   215.1 1008.01
   244.4  990.84   254.2   988.6   283.5   969.4   322.6  951.97   332.4  950.22
   361.7  931.88     440  899.48   479.1  889.98   508.4   886.4   547.5  873.51
   654.2  872.08   931.2  873.89   946.2  875.28  1049.2  903.17  1088.2  905.65
  1117.4  914.97  1136.8  926.23    1166  935.35  1234.2  948.33  1341.2  977.26
  1399.6  985.93  1428.8  983.75    1458  994.04  1477.5  997.52  1516.4  991.51
#Mann= 3 , 0 , 0
       0      .1       0   931.2    .045       0   946.2      .1       0
Bank Sta=931.2,946.2
XS Rating Curve= 0 ,0
Exp/Cntr=0.3,0.1

Type RM Length L Ch R = 1 ,36138.6 ,458.831,463.774,470.13
XS GIS Cut Line= 4
     1787912.938      332134.455      1788197.16      332707.716
     1788399.812      333116.455     1788628.398      333509.619
#Sta/Elev= 30
       0 1028.24    58.2 1011.35    67.9 1010.21   145.4  985.94   155.1  984.79
   203.6  970.54   232.7  951.41   242.4  948.13   271.5  929.12   290.8  920.11
   319.9  898.53   339.3  891.17   358.7  880.69     446  871.53   620.5  871.41
  1087.3  873.62  1102.3  876.88  1115.4  880.75  1144.5  898.92  1163.8  904.81
  1192.8   921.5  1221.9  933.38  1250.9  941.01  1299.3  957.74  1318.6  970.67
  1328.3  974.77    1367  975.57  1454.1  970.51  1531.5  970.54  1550.9  972.48
#Mann= 3 , 0 , 0
       0      .1       0  1087.3    .045       0  1102.3      .1       0
Bank Sta=1087.3,1102.3
XS Rating Curve= 0 ,0
Exp/Cntr=0.3,0.1

Type RM Length L Ch R = 1 ,35674.9 ,404.495,400,395.506
XS GIS Cut Line= 4
     1787702.204      332206.092     1787853.594      332821.436
     1787962.293      333263.261     1788070.993      333705.086
#Sta/Elev= 30
       0 1031.52      78  1008.6   146.2  984.25     195  971.81   224.2  956.79
     234  955.46   302.2  909.01   370.5  883.27   419.2   873.5  1020.9  870.41
  1081.2   870.6  1096.2  873.74  1117.7  880.83  1146.8  896.71  1166.1  900.96
  1175.8  905.72  1185.5  915.23  1195.2  919.37  1224.2  957.16  1233.9  962.62
  1262.9  971.43  1311.4  978.31  1340.4  980.71  1379.1  979.05  1398.5  980.56
  1466.2 1012.02  1485.6 1014.48  1495.3 1017.97  1524.3 1030.14  1543.7 1041.09
#Mann= 3 , 0 , 0
       0      .1       0  1081.2    .045       0  1096.2      .1       0
Bank Sta=1081.2,1096.2
XS Rating Curve= 0 ,0
Exp/Cntr=0.3,0.1

Type RM Length L Ch R = 1 ,35274.9 ,401.069,400,398.93
XS GIS Cut Line= 4
       1787099.8      332364.223     1787405.283      333013.957
     1787598.878      333425.717     1787792.474      333837.476
#Sta/Elev= 30
       0 1100.45    19.7 1084.29    39.3 1075.33    68.8 1053.39    88.5 1042.62
   108.2 1025.92     118 1023.18   147.5 1005.29   196.7  984.73   245.9  970.86
   295.1  950.34   314.7  936.63   363.9  910.76   442.6  876.18   599.9  871.51
  1066.5  870.21  1165.5  870.57  1180.5  875.88    1202  884.19  1250.4  914.65
  1269.8  939.09  1279.5  945.38  1318.2  963.41  1395.6  985.02    1444  977.04
  1463.4  978.98  1531.2 1004.53  1589.2 1016.88  1618.3 1035.67    1628 1038.77
#Mann= 3 , 0 , 0
       0      .1       0  1165.5    .045       0  1180.5      .1       0
Bank Sta=1165.5,1180.5
XS Rating Curve= 0 ,0
Exp/Cntr=0.3,0.1

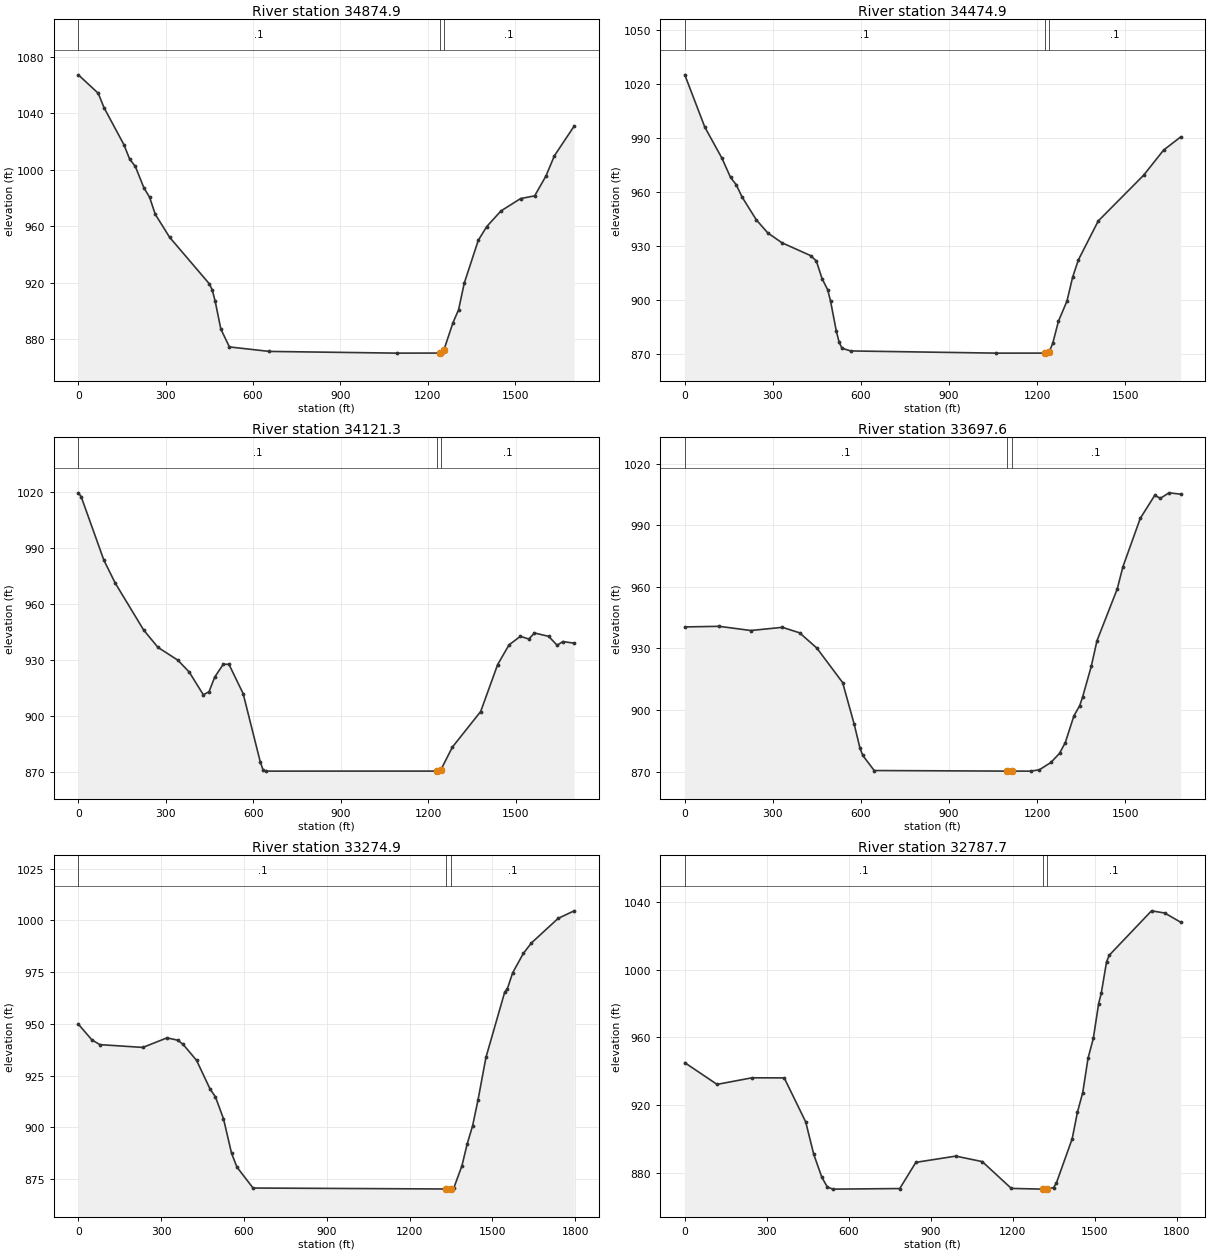
Type RM Length L Ch R = 1 ,34874.9 ,400.687,400,399.313
XS GIS Cut Line= 4
     1786657.519       332502.39      1787028.62      333203.154
     1787241.558      333605.251     1787454.496      334007.349
#Sta/Elev= 30
       0 1067.25    68.5 1054.18    88.1 1044.05   156.6 1017.78   176.2 1007.62
   195.8 1002.36   225.2  987.24   244.7   980.6   264.3  968.48   313.3   952.3
   450.3  919.19   460.1  914.84   469.9  907.09   489.5  887.26   518.9   874.6
   655.9  871.42  1093.1  870.21  1240.5  870.26  1255.5  872.38  1286.7  891.73
    1306  900.89  1325.4  919.68  1373.8  950.15  1402.9  959.85  1451.3  970.85
    1519  979.64  1567.4  981.57  1606.2  995.66  1635.2 1009.97    1703 1030.95
#Mann= 3 , 0 , 0
       0      .1       0  1240.5    .045       0  1255.5      .1       0
Bank Sta=1240.5,1255.5
XS Rating Curve= 0 ,0
Exp/Cntr=0.3,0.1

Type RM Length L Ch R = 1 ,34474.9 ,354.8,353.545,351.163
XS GIS Cut Line= 4
      1786280.28      332725.097     1786665.884      333402.388
     1786891.002      333797.795      1787116.12      334193.202
#Sta/Elev= 30
       0 1025.07    68.2  995.97   126.6  978.67   155.9  967.98   175.4  963.88
   194.8  957.18   243.6  944.41   282.5  937.15   331.2   931.6   428.7  924.48
   448.1  921.53   467.6   911.7   487.1  905.39   496.8  898.99   516.3  882.45
   526.1  876.13   535.8  872.93     565  871.43  1060.1  870.21  1226.9  870.22
  1241.9  871.04  1253.7  875.68  1273.1  887.96  1302.1  899.16  1321.5   912.5
  1340.9  922.05  1408.6  943.73  1563.5  969.23  1631.3  983.18  1689.4  990.49
#Mann= 3 , 0 , 0
       0      .1       0  1226.9    .045       0  1241.9      .1       0
Bank Sta=1226.9,1241.9
XS Rating Curve= 0 ,0
Exp/Cntr=0.3,0.1

Type RM Length L Ch R = 1 ,34121.3 ,428.704,423.736,419.895
XS GIS Cut Line= 4
     1785919.736      332944.956     1786348.044      333608.304
     1786594.694      333990.306     1786871.167       334353.74
#Sta/Elev= 30
       0 1019.43     9.7 1017.38    87.7  983.29   126.7     971   224.2  945.84
     273  936.59   341.2  929.72   380.2  923.39   428.9  911.12   448.4  912.79
   467.9  920.63   497.2   927.5   516.7  927.47   565.4  911.77   623.9  875.33
   633.6  870.89   643.4   870.2  1228.9  870.22  1243.9  870.96  1283.2  883.07
  1380.3  902.17  1438.6  927.36  1477.5   937.9  1516.4  942.46  1545.5  941.05
  1564.9  944.28  1613.5  942.47  1642.7   937.7  1662.1  939.68    1701  938.81
#Mann= 3 , 0 , 0
       0      .1       0  1228.9    .045       0  1243.9      .1       0
Bank Sta=1228.9,1243.9
XS Rating Curve= 0 ,0
Exp/Cntr=0.3,0.1

Type RM Length L Ch R = 1 ,33697.6 ,431.291,422.719,414.289
XS GIS Cut Line= 4
     1785467.732      333508.005     1786007.246      334004.809
     1786334.701      334306.341     1786683.134       334679.96
#Sta/Elev= 30
       0  940.44   117.3  940.73   224.9  938.69   332.5  940.24   391.2  937.56
   449.8  930.16   537.8  913.33   576.9  893.21   596.5  881.63   606.3  877.86
   645.4  870.49  1098.4  870.21  1113.4  870.21  1178.5   870.2    1208  870.85
  1247.3  874.41  1276.8  878.86  1296.4  884.09  1325.9  897.15  1345.6  902.12
  1355.4  906.31  1384.9  921.22  1404.5  933.75  1473.3  958.89  1492.9  969.79
  1551.9  993.32    1601 1004.47  1620.7 1003.12  1650.1 1005.75  1689.4 1005.11
#Mann= 3 , 0 , 0
       0      .1       0  1098.4    .045       0  1113.4      .1       0
Bank Sta=1098.4,1113.4
XS Rating Curve= 0 ,0
Exp/Cntr=0.3,0.1

Type RM Length L Ch R = 1 ,33274.9 ,482.356,487.201,491.903
XS GIS Cut Line= 4
     1784983.167      334135.644     1785798.823      334481.764
     1786217.682      334659.505     1786635.399      334839.882
#Sta/Elev= 30
       0   949.9    48.7  942.32    77.9  939.98   233.7  938.63   321.3  943.26
   360.3  942.11   379.7  940.08   428.4  932.36   477.1  918.55   496.6  914.73
   525.8  904.17     555  887.51   574.5  880.81   632.9  870.67  1333.6  870.21
  1348.6  870.15  1350.7  870.14  1360.4  870.78  1389.5  881.42  1408.8  892.08
  1428.2  900.75  1447.6  913.09  1476.6  933.83  1544.4  965.29    1554  966.94
  1573.4  974.72  1612.1  984.07  1641.2  989.11    1738 1000.99  1796.1 1004.65
#Mann= 3 , 0 , 0
       0      .1       0  1333.6    .045       0  1348.6      .1       0
Bank Sta=1333.6,1348.6
XS Rating Curve= 0 ,0
Exp/Cntr=0.3,0.1

Type RM Length L Ch R = 1 ,32787.7 ,371.757,369.053,366.349
XS GIS Cut Line= 4
     1784894.055      334314.712     1785632.319       334837.67
     1786003.605      335100.675     1786374.892       335363.68
#Sta/Elev= 30
       0     945     118  932.17   245.8  936.06   363.9  936.01   442.5  909.97
     472  890.78   501.5  877.24   521.2   871.6   540.9  870.21   786.7  870.55
   845.7  886.05   991.8  889.74  1088.7  886.49  1195.1  870.63    1310  870.21
    1325  870.21    1350  871.15  1359.7  873.72  1417.8     900  1437.2  915.83
  1456.5  927.36  1475.9  947.67  1495.3  959.47  1514.6  979.89  1524.3  986.16
  1543.7 1004.74  1553.3 1008.54  1708.2 1034.83  1756.6 1033.54  1814.7 1028.11
#Mann= 3 , 0 , 0
       0      .1       0    1310    .045       0    1325      .1       0
Bank Sta=1310,1325
XS Rating Curve= 0 ,0
Exp/Cntr=0.3,0.1

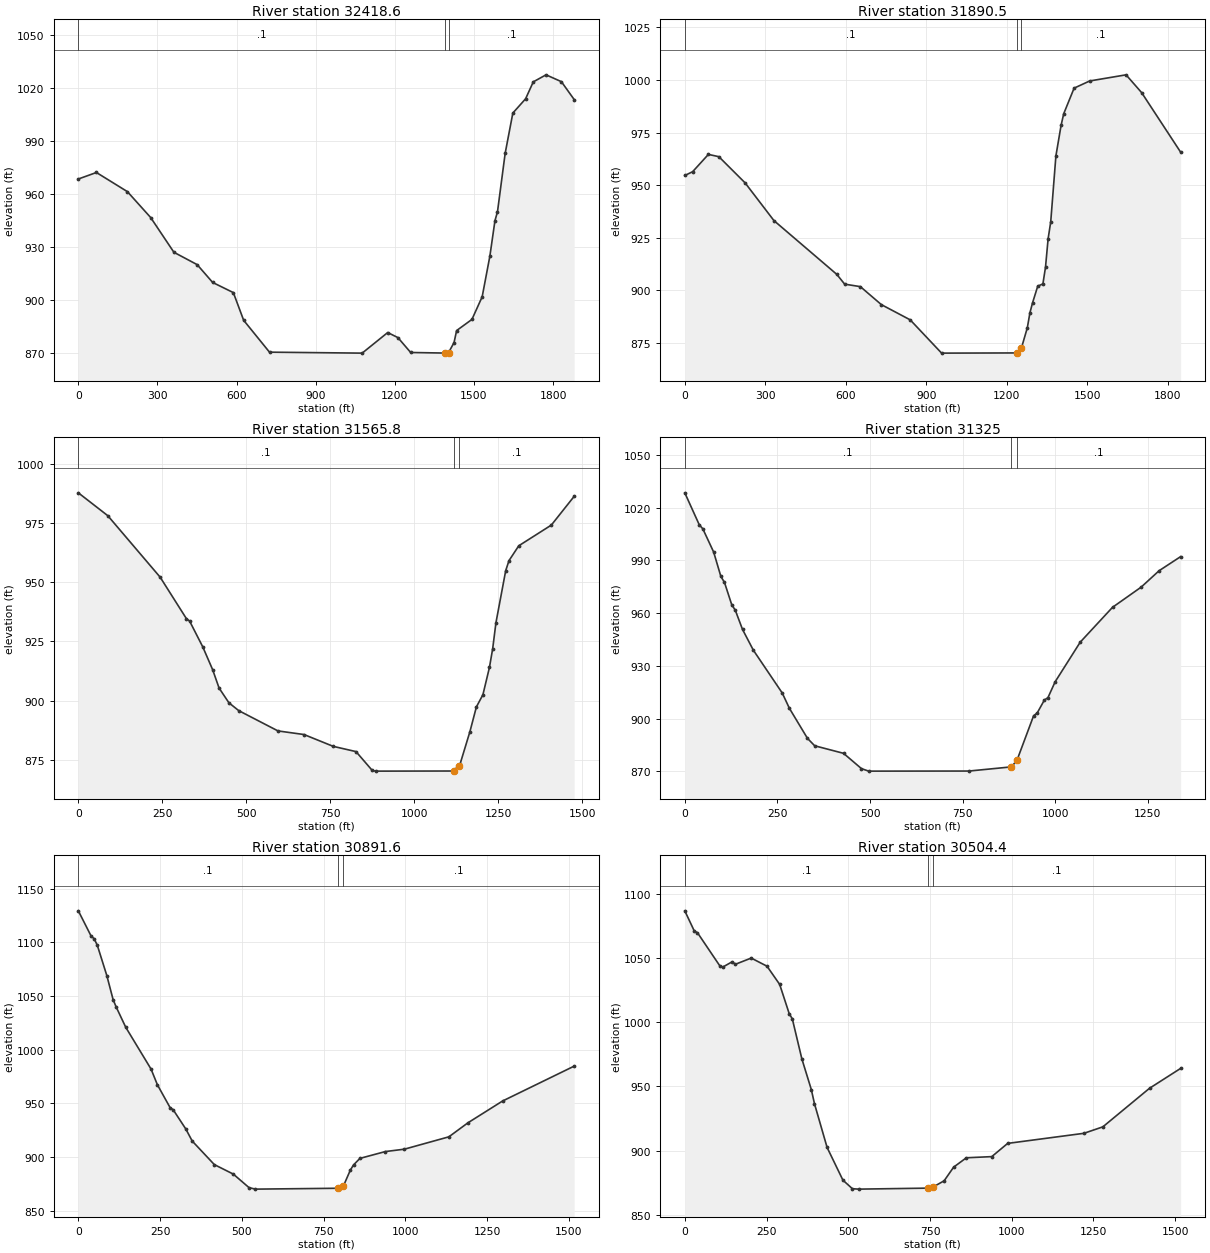
Type RM Length L Ch R = 1 ,32418.6 ,535.328,528.105,520.883
XS GIS Cut Line= 4
      1784531.21      334714.976     1785384.583      335175.674
       1785784.9      335391.787     1786189.436      335600.965
#Sta/Elev= 30
       0   968.6    68.6  972.28   186.1  961.45   274.3  946.82   362.4  927.18
   450.6  920.19   509.4  910.12   587.8  904.38   626.9  888.73   724.9  870.71
  1076.3  870.17  1173.1  881.81  1211.8  878.95  1260.2  870.53    1389  870.21
    1404  870.52  1424.7  876.16  1434.4  882.92  1492.5  889.23  1531.3  902.02
  1560.4  924.91  1579.8  945.05  1589.4  950.11  1618.5  983.12  1647.6 1005.88
    1696 1013.95  1725.1 1023.51  1773.5 1027.49  1831.7 1023.62  1880.1 1013.53
#Mann= 3 , 0 , 0
       0      .1       0    1389    .045       0    1404      .1       0
Bank Sta=1389,1404
XS Rating Curve= 0 ,0
Exp/Cntr=0.3,0.1

Type RM Length L Ch R = 1 ,31890.5 ,325.768,324.729,323.69
XS GIS Cut Line= 4
     1784411.424      335673.268     1785334.345       335837.42
     1785782.315      335917.097     1786230.284      335996.774
#Sta/Elev= 30
       0  954.62    29.3  956.43    87.9  964.65   126.9  963.56   224.6  951.13
     332   933.2   566.3  907.63   595.6  902.98   654.2  901.79   732.3  893.25
   839.8  886.01   956.8  870.19  1238.9  870.28  1253.9  872.47  1276.2  882.22
  1285.9  889.36  1295.6  894.06    1315  902.01  1334.3  903.11    1344  911.07
  1353.7  924.55  1363.4  932.56  1382.7  963.92  1402.1  978.52  1411.8  983.97
  1450.5  996.14  1508.6  999.55  1644.1 1002.47  1702.2     994  1847.4  965.72
#Mann= 3 , 0 , 0
       0      .1       0  1238.9    .045       0  1253.9      .1       0
Bank Sta=1238.9,1253.9
XS Rating Curve= 0 ,0
Exp/Cntr=0.3,0.1

Type RM Length L Ch R = 1 ,31565.8 ,249.274,240.773,232.273
XS GIS Cut Line= 4
     1784484.942       336020.78     1785041.429      336119.758
     1785489.254      336199.409     1785941.738      336254.536
#Sta/Elev= 30
       0  987.76    87.7   978.1   243.6  952.12   321.6  934.64   331.3  933.57
   370.3  922.72   399.6  913.13     419  905.29   448.3  899.06   477.5  895.76
   594.3  887.19   671.7  885.67   758.8  880.67   826.5  878.46   874.9   870.5
   884.6  870.21  1116.9  870.26  1131.9  872.43  1136.5  873.29  1165.6  886.88
  1184.9  897.34  1204.3  902.48  1223.7  913.99  1233.4  921.95  1243.1  932.91
  1272.2  954.92  1281.9  959.12    1311  965.39    1408  974.14  1475.9  986.27
#Mann= 3 , 0 , 0
       0      .1       0  1116.9    .045       0  1131.9      .1       0
Bank Sta=1116.9,1131.9
XS Rating Curve= 0 ,0
Exp/Cntr=0.3,0.1

Type RM Length L Ch R = 1 ,31325   ,440.133,433.383,425.537
XS GIS Cut Line= 4
     1784744.067      336664.943     1785160.118      336562.282
     1785601.869      336453.279     1786043.619      336344.276
#Sta/Elev= 30
       0 1028.34      39  1010.2    48.7 1007.88    77.9  994.68    97.4  980.82
   107.1  977.45   126.6  964.83   136.4  961.58   155.8  950.73     185  938.94
     263  914.61   282.4  905.89   331.1  888.84   350.6  884.61   428.5  880.32
   476.9  871.62   496.3   870.2   767.4  870.25   881.8  872.62   896.8  876.41
   941.6  901.65   951.3  903.23   970.7   910.6   980.3  911.93   999.7  920.95
  1067.5  943.49  1154.6  963.27    1232  974.76  1280.4  984.08  1338.5  992.09
#Mann= 3 , 0 , 0
       0      .1       0   881.8    .045       0   896.8      .1       0
Bank Sta=881.8,896.8
XS Rating Curve= 0 ,0
Exp/Cntr=0.3,0.1

Type RM Length L Ch R = 1 ,30891.6 ,392.244,387.21,383.272
XS GIS Cut Line= 5
     1784932.429      337282.313     1785234.672      337109.255
     1785629.249      336883.328     1786015.292        336639.1
     1786232.427      336501.731
#Sta/Elev= 30
       0  1129.3    38.7 1106.04    48.4 1103.26      58 1097.27    87.1 1069.05
   106.4 1046.57   116.1 1039.53   145.1 1020.81   222.5  981.89   241.9  967.27
   280.6  946.08   290.2  944.01   328.9  926.05   348.3  914.92     416  892.96
     474  884.12   522.4  871.45   541.8  870.11   793.1  870.91   808.1  873.38
   812.7   874.3   832.1  887.85   841.8  892.64   861.3  898.73     939  905.09
   997.3  907.31  1133.4  918.81  1191.7  931.86  1297.8  952.19  1516.7  984.66
#Mann= 3 , 0 , 0
       0      .1       0   793.1    .045       0   808.1      .1       0
Bank Sta=793.1,808.1
XS Rating Curve= 0 ,0
Exp/Cntr=0.3,0.1

Type RM Length L Ch R = 1 ,30504.4 ,314.604,308.66,302.716
XS GIS Cut Line= 5
     1785222.519      337757.465     1785473.267      337515.752
     1785800.619      337200.196      1786115.22      336868.983
     1786292.172      336682.688
#Sta/Elev= 30
       0 1086.65      29 1070.97    38.7 1069.64   106.4 1044.11   116.1 1042.88
   145.1 1047.03   154.8 1045.07   203.2 1049.89   251.5 1043.56   290.2  1029.4
   319.3 1006.71   328.9 1002.58     358  971.53     387  947.59   396.7  936.54
   435.3  902.53   483.7  877.08   512.7  870.42   532.1  870.11     745  870.89
     760  871.85   793.3  876.59   822.4  887.22   861.3   894.5     939   895.4
   987.6  905.69  1220.9  913.54  1278.8  918.57  1421.5  948.57  1516.7  964.05
#Mann= 3 , 0 , 0
       0      .1       0     745    .045       0     760      .1       0
Bank Sta=745,760
XS Rating Curve= 0 ,0
Exp/Cntr=0.3,0.1

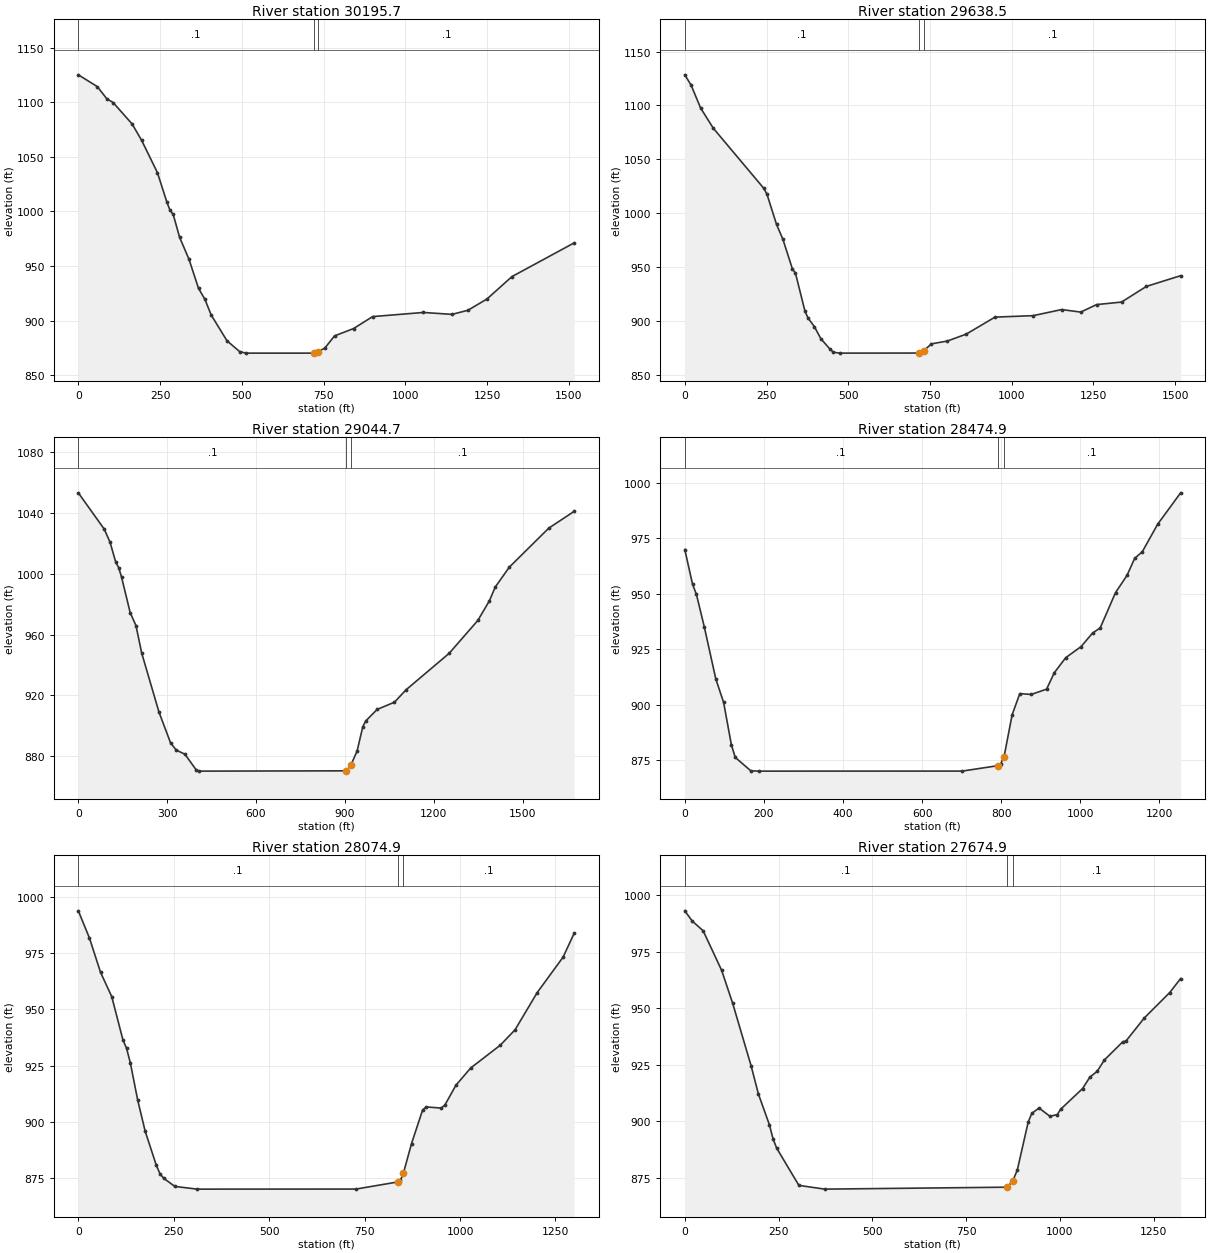
Type RM Length L Ch R = 1 ,30195.7 ,556.821,557.239,557.657
XS GIS Cut Line= 5
      1785650.36      338004.858     1785830.129      337706.557
     1786064.816      337317.126      1786283.14      336915.865
     1786405.939       336690.17
#Sta/Elev= 30
       0  1125.2      58 1114.41    87.1 1103.26   106.4 1099.81   164.5 1080.16
   193.5 1065.22   241.9 1035.58   270.9 1008.48   280.6 1000.95   290.2  997.23
   309.6  976.46   338.6  956.06   367.6  929.51     387  919.54   406.3  905.12
   454.7  881.43   493.4  871.53   512.7  870.11   719.5  870.11   734.5  871.47
   754.6  874.92   783.6  885.89   841.8  892.62   900.2   903.6  1055.7  907.38
  1143.1  905.63  1191.7  909.38  1250.1  919.76  1326.4  940.26  1516.7  971.16
#Mann= 3 , 0 , 0
       0      .1       0   719.5    .045       0   734.5      .1       0
Bank Sta=719.5,734.5
XS Rating Curve= 0 ,0
Exp/Cntr=0.3,0.1

Type RM Length L Ch R = 1 ,29638.5 ,594.028,593.798,593.567
XS GIS Cut Line= 5
      1786144.18      338243.803     1786323.949      337945.502
     1786558.636      337556.072      1786776.96       337154.81
     1786899.759      336929.115
#Sta/Elev= 30
       0 1128.42    19.3 1118.84    48.4 1097.59    87.1 1078.89   241.9 1022.97
   251.5 1017.43   280.6  989.59   299.9  975.92   328.9  948.56   338.6  944.24
   367.6  909.01   377.3  902.52   396.7  894.59     416  883.56     445  873.53
   454.7  870.96     474  870.11   716.5  870.19   731.5  872.52   754.6  878.73
     803  881.32   861.3  887.81   948.8  903.53  1065.4  904.89  1152.9  910.54
  1211.2   908.2  1259.8  915.17  1335.9  917.49    1412  932.04  1516.7  941.99
#Mann= 3 , 0 , 0
       0      .1       0   716.5    .045       0   731.5      .1       0
Bank Sta=716.5,731.5
XS Rating Curve= 0 ,0
Exp/Cntr=0.3,0.1

Type RM Length L Ch R = 1 ,29044.7 ,565.298,569.848,574.397
XS GIS Cut Line= 5
     1786601.618      338382.943     1786881.487      337961.432
     1787116.175      337572.001     1787334.499       337170.74
     1787457.298      336945.045
#Sta/Elev= 30
       0 1053.41    87.6 1029.47     107 1020.93   126.5 1007.65   136.2 1004.17
     146  997.85   175.1  974.49   194.6  965.96   214.1  947.77   272.4  908.94
   311.4  888.73   330.8  883.89     360  881.23   398.9  870.65   408.7  870.08
   905.5  870.28   920.5  874.13   941.3  883.25   960.6  899.29   970.4  903.09
  1009.2  910.73  1067.6  915.49  1106.4   923.6  1252.2  947.66  1349.4  969.42
  1388.3  982.34  1407.7  991.26  1455.5 1004.47  1588.7 1030.15  1674.4  1041.2
#Mann= 3 , 0 , 0
       0      .1       0   905.5    .045       0   920.5      .1       0
Bank Sta=905.5,920.5
XS Rating Curve= 0 ,0
Exp/Cntr=0.3,0.1

Type RM Length L Ch R = 1 ,28474.9 ,399.849,400,400.151
XS GIS Cut Line= 4
      1787039.53      338479.166     1787272.683      338226.821
     1787581.457      337892.631     1787890.232       337558.44
#Sta/Elev= 30
       0  969.98    19.6  954.33    29.4  949.75    49.1  935.25    78.5  911.59
    98.2  901.04   117.8  881.94   127.6  876.28   166.9  870.25   186.5  870.11
   701.8  870.13   791.1  872.56   798.6  873.26   806.1  876.59   808.2  877.52
   827.6  895.49     847  905.05     876  904.66   914.7  907.05   934.1  914.42
   963.1  921.24  1001.9  926.23  1030.9  932.33  1050.3  934.65    1089  950.56
    1118  958.31  1137.4  965.98  1156.8  969.01  1195.5  981.37  1253.6  995.53
#Mann= 3 , 0 , 0
       0      .1       0   791.1    .045       0   806.1      .1       0
Bank Sta=791.1,806.1
XS Rating Curve= 0 ,0
Exp/Cntr=0.3,0.1

Type RM Length L Ch R = 1 ,28074.9 ,397.798,400,402.202
XS GIS Cut Line= 4
     1787294.662      338784.028     1787560.483      338500.178
     1787871.496       338168.07     1788182.509      337835.962
#Sta/Elev= 30
       0  993.71    29.2  981.59    58.3  966.34    87.5  955.61   116.7  936.48
   126.4  932.58   136.1  926.29   155.6  909.58     175  895.89   204.2  880.74
   213.9  876.92   223.6  874.94   252.8  871.32   311.1  870.11   727.7  870.14
   836.4  873.29   843.9     874   851.4  877.09   872.9  890.36     902   905.3
   911.7  906.61   950.4  906.11   960.1   907.4   989.1  916.24  1027.8   923.9
  1105.3  934.03    1144  940.86  1202.1  957.41  1269.8  973.12  1298.9  983.73
#Mann= 3 , 0 , 0
       0      .1       0   836.4    .045       0   851.4      .1       0
Bank Sta=836.4,851.4
XS Rating Curve= 0 ,0
Exp/Cntr=0.3,0.1

Type RM Length L Ch R = 1 ,27674.9 ,398.535,400,401.465
XS GIS Cut Line= 4
     1787497.906      339026.887     1787807.778      338754.881
     1788149.726      338454.719     1788491.673      338154.557
#Sta/Elev= 30
       0  993.02    19.6  988.56    49.1  984.17    98.2  966.76   127.6  952.22
   176.7  924.65   196.3  912.13   225.8  898.46   235.6  892.16   245.4  888.09
   304.3  871.76   373.1  870.11   859.8  870.97   874.8  873.78   886.7  878.52
   915.7  899.67   925.4  903.57   944.8  905.94   973.8  902.27   993.2  903.04
  1002.9  905.47  1060.9  914.54  1080.3  919.58  1099.7  922.13    1119  927.15
  1167.4  935.08  1177.1  935.63  1225.5  945.72  1293.3  956.94  1322.3  963.11
#Mann= 3 , 0 , 0
       0      .1       0   859.8    .045       0   874.8      .1       0
Bank Sta=859.8,874.8
XS Rating Curve= 0 ,0
Exp/Cntr=0.3,0.1

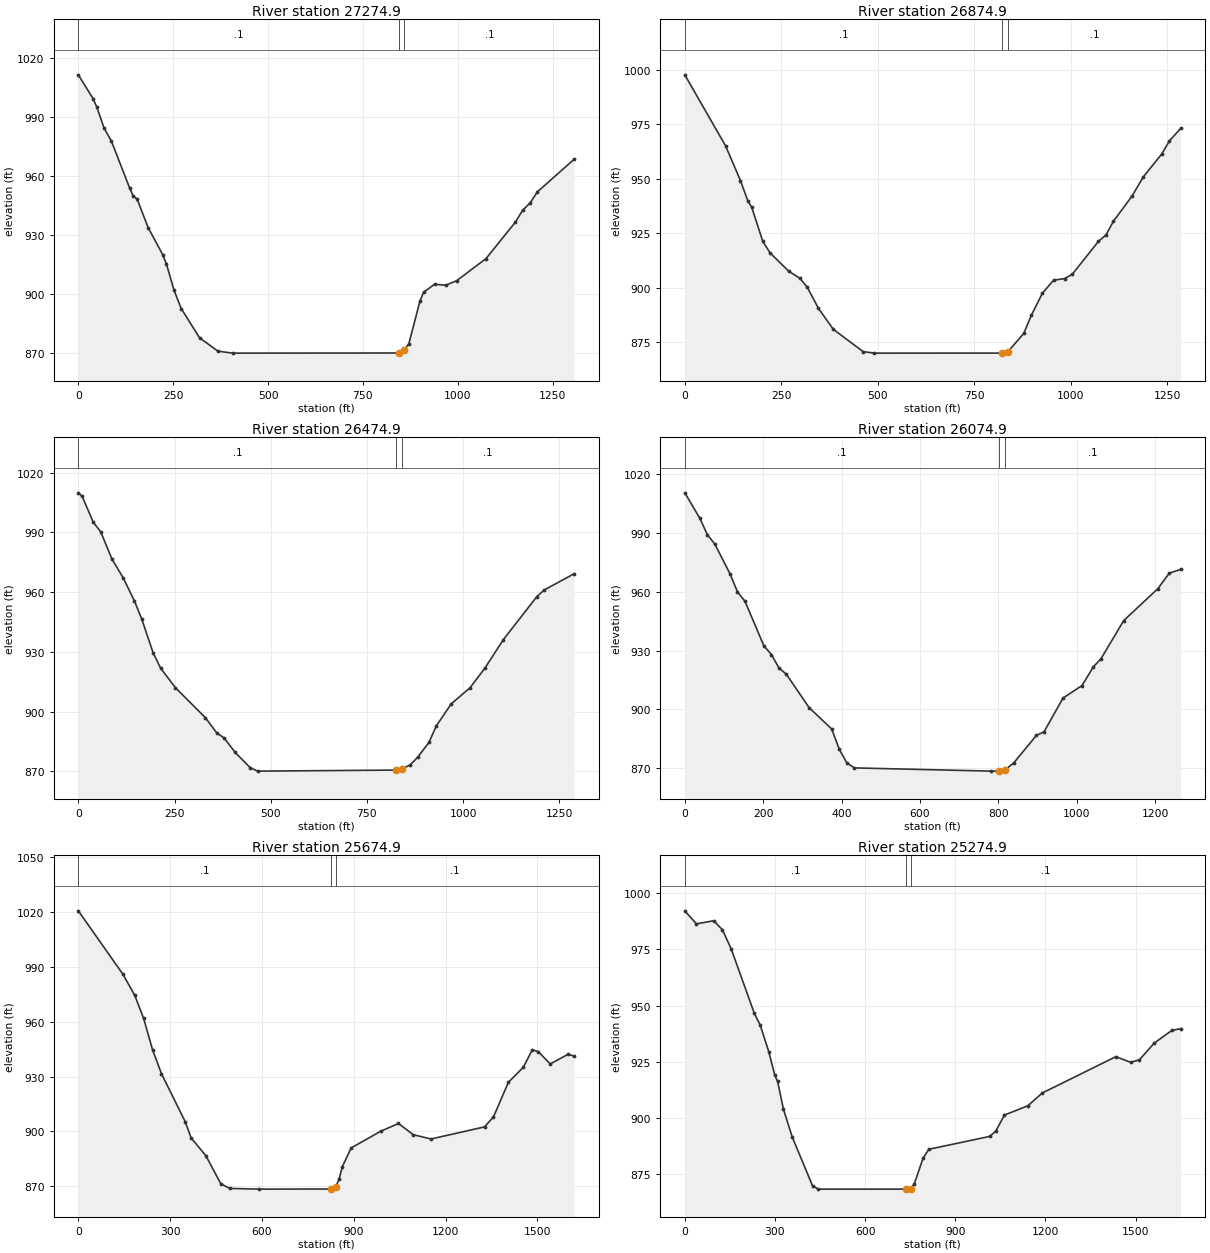
Type RM Length L Ch R = 1 ,27274.9 ,398.492,400,401.284
XS GIS Cut Line= 4
     1787718.548      339290.535     1788033.235      339048.644
     1788393.976      338771.351     1788754.716      338494.059
#Sta/Elev= 30
       0 1011.59    38.7  999.51    48.4  995.33    67.8  984.53    87.1   977.9
   135.5  953.93   145.2  949.86   154.9  948.48   183.9  933.97   222.7  920.07
   232.3  915.39   251.7  902.37   271.1  892.78   319.5  877.92   367.9  871.11
   406.6  870.11   844.4  870.18   859.4  871.83   871.3  874.94   900.3  896.49
     910  901.04     939  905.14   968.1  904.64   997.1  906.91  1074.6  918.19
    1152  936.71  1171.4  942.79  1190.7  946.44  1210.1  952.11  1306.9  968.67
#Mann= 3 , 0 , 0
       0      .1       0   844.4    .045       0   859.4      .1       0
Bank Sta=844.4,859.4
XS Rating Curve= 0 ,0
Exp/Cntr=0.3,0.1

Type RM Length L Ch R = 1 ,26874.9 ,405.528,400,394.23
XS GIS Cut Line= 4
     1787939.471       339554.52     1788251.636      339346.194
     1788630.094      339093.626     1789006.052      338837.295
#Sta/Elev= 30
       0  997.73   105.9   965.1   144.3  949.22   163.6  939.82   173.2   937.1
   202.1  921.38   221.3  916.02   269.4  907.67   298.3  904.44   317.6  900.28
   346.4  890.67     385  881.03   462.4  870.79   491.5  870.11   822.8  870.13
   837.8  870.82   878.7  879.15   898.1  887.38   927.1  897.62   956.1  903.55
   985.2  904.32  1004.6  906.31  1072.3  921.37  1091.7  924.27  1111.1  930.59
  1159.5  942.17  1188.5  950.91  1236.9  961.56  1256.3  967.45  1285.3  973.12
#Mann= 3 , 0 , 0
       0      .1       0   822.8    .045       0   837.8      .1       0
Bank Sta=822.8,837.8
XS Rating Curve= 0 ,0
Exp/Cntr=0.3,0.1

Type RM Length L Ch R = 1 ,26474.9 ,394.752,400,405.713
XS GIS Cut Line= 4
     1788325.667       340015.99     1788580.369      339735.622
     1788886.397      339398.755     1789185.302      339055.736
#Sta/Elev= 30
       0 1009.87     9.7 1008.21    38.8  995.11    58.3  990.27    87.4  976.61
   116.5   967.2   145.7  955.64   165.1  946.33   194.2  929.66   213.7  921.89
   252.5  911.98   330.2  896.97   359.4  889.39   378.8  886.79   407.8   879.5
   446.6  871.86   465.9  870.11   826.4  870.64   841.4  871.23   862.9  873.27
   882.3  877.13   911.3  884.49   930.7  892.85   969.4  903.92  1017.8  911.88
  1056.6  921.76    1105   936.2  1192.1  957.79  1211.4  961.11  1288.9  969.25
#Mann= 3 , 0 , 0
       0      .1       0   826.4    .045       0   841.4      .1       0
Bank Sta=826.4,841.4
XS Rating Curve= 0 ,0
Exp/Cntr=0.3,0.1

Type RM Length L Ch R = 1 ,26074.9 ,395.42,400,404.58
XS GIS Cut Line= 4
     1788458.448      340174.653      1788751.75      339973.772
     1789127.145      339716.666      1789502.54       339459.56
#Sta/Elev= 30
       0  1010.5    38.4  997.55    57.6  989.11    76.9  984.26   115.3  969.22
   134.5  959.96   153.7  955.14   201.8  932.46     221     928   240.2  921.21
   259.4  917.92   317.1  900.96   374.9  890.03   394.2  879.68   413.6   872.7
   432.9  870.17   781.5  868.52     803  868.54     818   869.3   839.5  872.72
   897.6  886.76     917  888.62   965.4   905.8  1013.8  912.19  1042.8  921.71
  1062.2  925.85  1120.3  945.34  1207.4  961.61  1236.5   969.5  1265.5  971.41
#Mann= 3 , 0 , 0
       0      .1       0     803    .045       0     818      .1       0
Bank Sta=803,818
XS Rating Curve= 0 ,0
Exp/Cntr=0.3,0.1

Type RM Length L Ch R = 1 ,25674.9 ,397.241,400,402.758
XS GIS Cut Line= 5
     1788531.418      340398.692     1788880.277      340252.372
     1789299.864      340076.385     1789719.452      339900.399
     1790025.658      339771.968
#Sta/Elev= 30
       0 1020.59   145.5  985.96   184.3  974.44   213.4  961.77   242.5  944.67
   271.6   931.6   349.2  905.35   368.6  896.46     417  886.67   465.4  871.43
   494.5  868.84   591.3  868.45   825.8  868.52   840.8  869.53   852.7  874.17
   862.3  880.53   891.4  890.94   988.2   900.1  1046.3  904.33  1094.7   898.2
  1152.8  895.87  1327.4  902.47  1356.7  907.92  1405.5  926.85  1454.3  935.07
  1483.6  944.64  1503.2   943.6  1542.2  936.89  1600.8  942.17  1620.4  941.17
#Mann= 3 , 0 , 0
       0      .1       0   825.8    .045       0   840.8      .1       0
Bank Sta=825.8,840.8
XS Rating Curve= 0 ,0
Exp/Cntr=0.3,0.1

Type RM Length L Ch R = 1 ,25274.9 ,403.514,400,396.486
XS GIS Cut Line= 5
      1788706.32      340658.311     1788984.929      340579.818
      1789422.88      340456.433     1789860.831      340333.047
     1790294.638       340210.83
#Sta/Elev= 30
       0  992.14    38.6  986.34    96.5  987.74   125.4  983.67   154.4  975.21
   231.6  946.46   250.9  941.31   279.8  929.33   299.1  919.16   308.8   916.2
   328.2  903.93   357.2  891.62     425  869.82   444.3  868.31     737  868.31
     752  868.38   763.8  870.69   792.9  882.04   812.2  886.04  1015.5  891.79
  1034.9  894.18  1063.9  901.28  1141.4  905.38  1189.8   911.1  1434.6  927.25
  1483.6  924.74    1513  925.86    1562  933.25  1620.8  938.91  1650.1  939.72
#Mann= 3 , 0 , 0
       0      .1       0     737    .045       0     752      .1       0
Bank Sta=737,752
XS Rating Curve= 0 ,0
Exp/Cntr=0.3,0.1

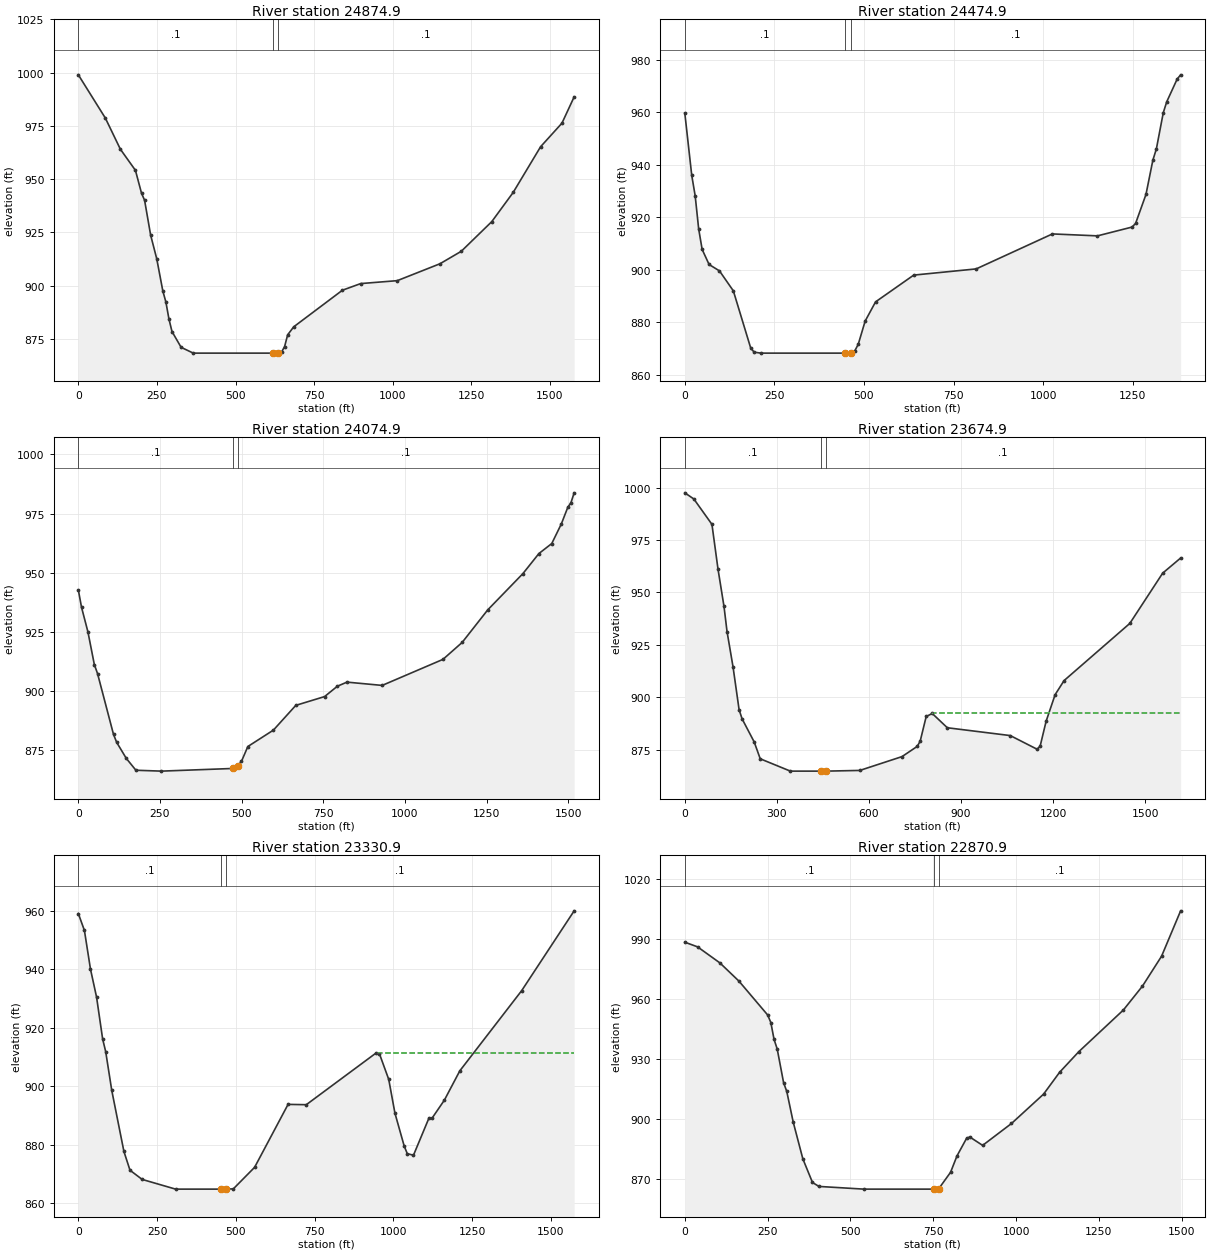
Type RM Length L Ch R = 1 ,24874.9 ,401.961,400,398.038
XS GIS Cut Line= 5
     1788997.429      341090.428     1789153.687      341018.644
     1789567.145      340828.703     1789980.603      340638.762
       1790430.3      340432.173
#Sta/Elev= 30
       0  998.92      86   978.6   133.7  964.01   181.6   954.1     201  943.33
   210.7  940.06     230  923.66   249.4  912.55   268.8   897.4   278.4  892.34
   288.1  884.36   297.8  878.46   326.9  871.03   365.6  868.31   619.5  868.31
   634.5  868.31   646.3  868.82     656  871.41   665.7   876.9     685  880.66
   839.9  897.84     898  900.95  1014.2  902.32  1149.9  910.24  1217.8   916.1
  1314.8  930.02  1382.8  943.71  1470.1  965.18    1538  976.24  1576.8  988.58
#Mann= 3 , 0 , 0
       0      .1       0   619.5    .045       0   634.5      .1       0
Bank Sta=619.5,634.5
XS Rating Curve= 0 ,0
Exp/Cntr=0.3,0.1

Type RM Length L Ch R = 1 ,24474.9 ,394.334,400,407.93
XS GIS Cut Line= 4
      1789352.43      341410.362     1789747.794      341185.167
     1790143.157      340959.973     1790554.818      340725.496
#Sta/Elev= 30
       0  959.79    19.4  936.03      29  928.22    38.7  915.65    48.4  907.83
    67.8  902.08    96.8  899.64   135.5  892.03   183.9  870.27   193.6  868.66
     213  868.31   447.5  868.31   462.5  868.39   474.4  869.18     484  871.64
   503.4  880.54   532.4  887.84   638.9  898.04   813.2   900.4    1026  913.73
  1151.7  912.99  1248.4  916.35  1258.1  917.72  1287.1  928.77  1306.4  941.87
  1316.1  946.11  1335.4  959.92  1345.1   964.1  1374.1  972.73  1383.8  974.35
#Mann= 3 , 0 , 0
       0      .1       0   447.5    .045       0   462.5      .1       0
Bank Sta=447.5,462.5
XS Rating Curve= 0 ,0
Exp/Cntr=0.3,0.1

Type RM Length L Ch R = 1 ,24074.9 ,401.164,400,395.409
XS GIS Cut Line= 4
     1789473.434      341653.717     1789936.769      341529.087
     1790381.115      341455.725     1790961.104      341359.969
#Sta/Elev= 30
       0   942.7     9.8  935.38    29.4  924.97      49  911.18    58.8  907.37
   107.7  881.66   117.5  878.28   146.9  871.52   176.3  866.52   254.6  866.15
   472.3  867.27   487.3  868.27   499.4  870.27     519  876.55   597.3  883.49
   665.8  893.94   753.9  897.65   793.1  902.03   822.5  903.76   930.2  902.37
  1116.3  913.37  1175.1  920.53  1253.5   934.3  1361.2  949.63  1410.2  958.11
  1449.4  962.31  1478.8  970.62  1498.4  977.58  1508.2  979.58    1518  983.75
#Mann= 3 , 0 , 0
       0      .1       0   472.3    .045       0   487.3      .1       0
Bank Sta=472.3,487.3
XS Rating Curve= 0 ,0
Exp/Cntr=0.3,0.1

Type RM Length L Ch R = 1 ,23674.9 ,347.145,343.981,340.425
XS GIS Cut Line= 4
     1789538.792      342063.286     1789968.353       341922.61
     1790408.668      341752.758     1791053.374      341504.062
#Sta/Elev= 30
       0  997.51    29.5  994.57    88.4  982.48   108.1  961.21   127.7  943.31
   137.6  931.34   157.2  914.45   176.9  894.06   186.7  889.72     226  878.73
   245.7  870.69   343.9  864.81   444.5  864.81   459.5  864.81     570  865.14
   707.6  871.74   756.8  876.58   766.6  879.04   786.3  890.86     806  892.29
   855.1  885.49  1060.2  881.76  1147.8  875.23  1157.5  876.78    1177  888.65
  1206.2  901.27  1235.4  907.99  1449.5  935.24  1556.6  959.22    1615  966.42
#Mann= 3 , 0 , 0
       0      .1       0   444.5    .045       0   459.5      .1       0
#XS Ineff= 2 , 0
                          806.73          892.34
Permanent Ineff=
       F       F
Bank Sta=444.5,459.5
XS Rating Curve= 0 ,0
Exp/Cntr=0.3,0.1

Type RM Length L Ch R = 1 ,23330.9 ,447.886,460.019,474.546
XS GIS Cut Line= 4
     1789759.416       342388.79      1790175.08      342184.761
     1790566.763      341956.025     1791134.294      341624.598
#Sta/Elev= 30
       0  959.07    19.3   953.3    38.6  940.05    57.9  930.48    77.2  916.14
    86.8  911.87   106.1  898.57   144.7  877.69     164  871.27   202.6  868.13
   308.7  864.81   453.6  864.81   468.6  864.81     492   864.9   559.5  872.27
   665.7   893.8   723.6  893.69     946  911.45   955.9  911.06   985.3  902.33
  1004.9  890.81  1034.3  879.56  1044.1  876.94  1063.8  876.41  1112.8  889.09
  1122.6  889.06  1161.8  895.24  1210.9  905.28  1407.1  932.69  1573.8  960.01
#Mann= 3 , 0 , 0
       0      .1       0   453.6    .045       0   468.6      .1       0
#XS Ineff= 2 , 0
                          946.68          911.47
Permanent Ineff=
       F       F
Bank Sta=453.6,468.6
XS Rating Curve= 0 ,0
Exp/Cntr=0.3,0.1

Type RM Length L Ch R = 1 ,22870.9 ,391.995,396,400.196
XS GIS Cut Line= 5
     1789588.027      342543.368     1789894.864      342568.099
     1790349.053      342604.707     1790800.533       342660.25
      1791076.71      342694.227
#Sta/Elev= 30
       0  988.48    38.5  986.14   105.8  978.12   163.5  968.97   250.1  952.02
   259.7  948.24   269.4  939.82     279  934.92   298.2  918.12   307.8  913.73
   327.2   898.4   356.3  879.98   385.4  868.15   404.8  866.16   540.5  864.81
   751.8  864.81   766.8  865.09   802.2  873.24   821.6  881.46   850.6  890.28
   860.3  890.91     899  886.72   986.1  897.68  1082.9  912.38  1131.3  923.32
  1189.3  933.65  1323.9  954.53  1381.5   966.5  1439.1  981.45  1496.6 1004.18
#Mann= 3 , 0 , 0
       0      .1       0   751.8    .045       0   766.8      .1       0
Bank Sta=751.8,766.8
XS Rating Curve= 0 ,0
Exp/Cntr=0.3,0.1