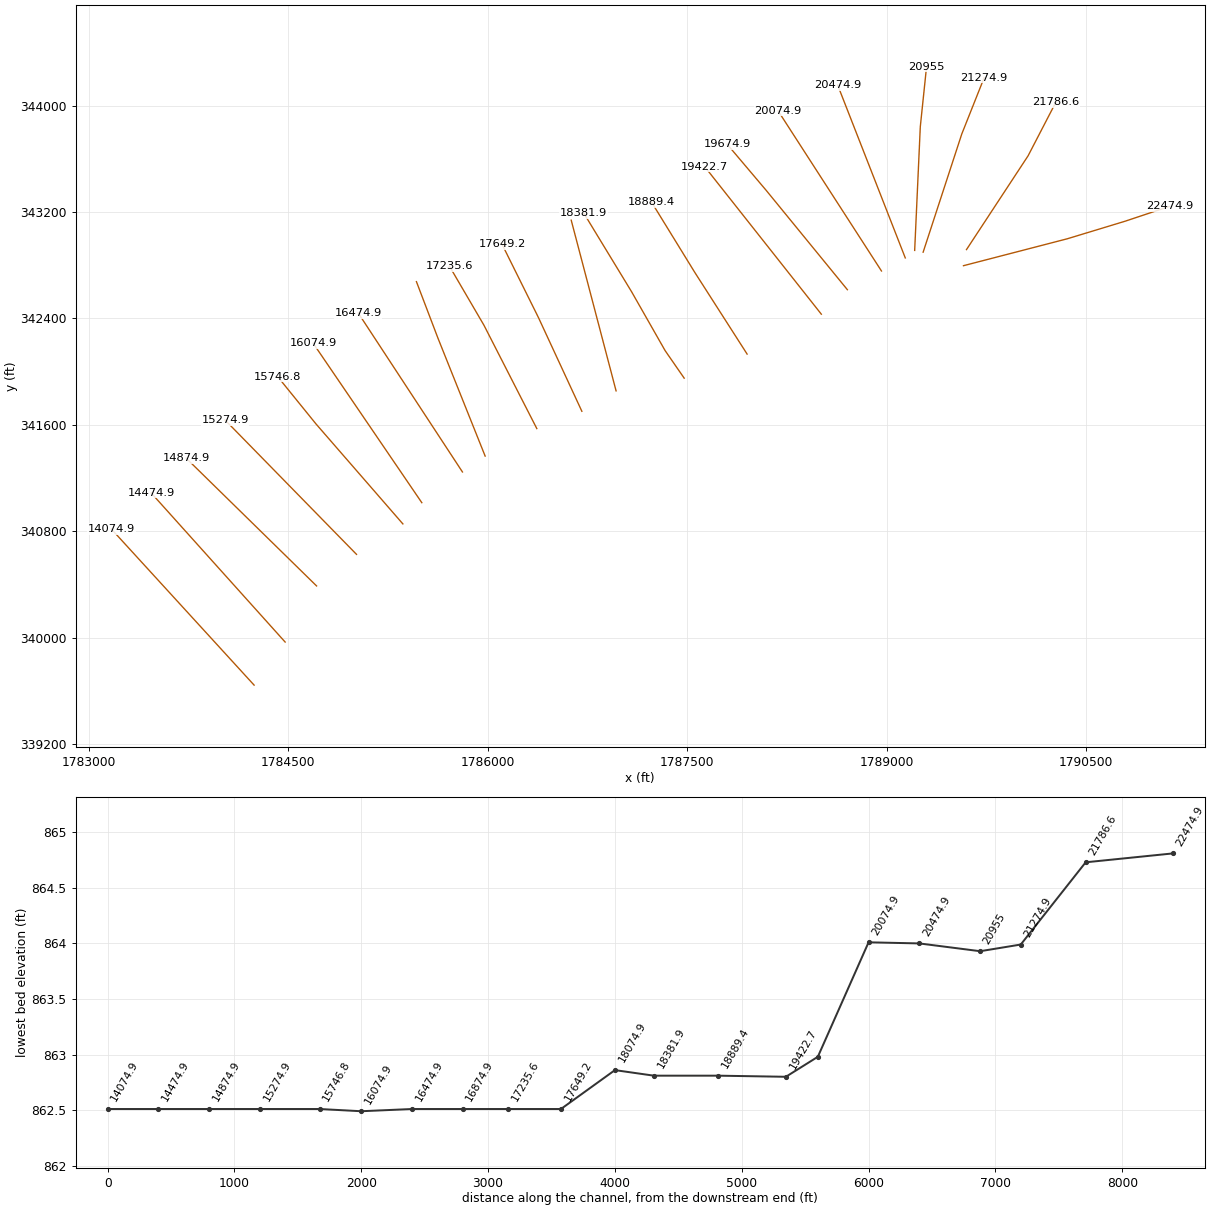
HEC-RAS study TygrtVlyRv.prj: TygrtVlyRv

--- TygrtVlyRv.g01 (geometry) --- (continued)

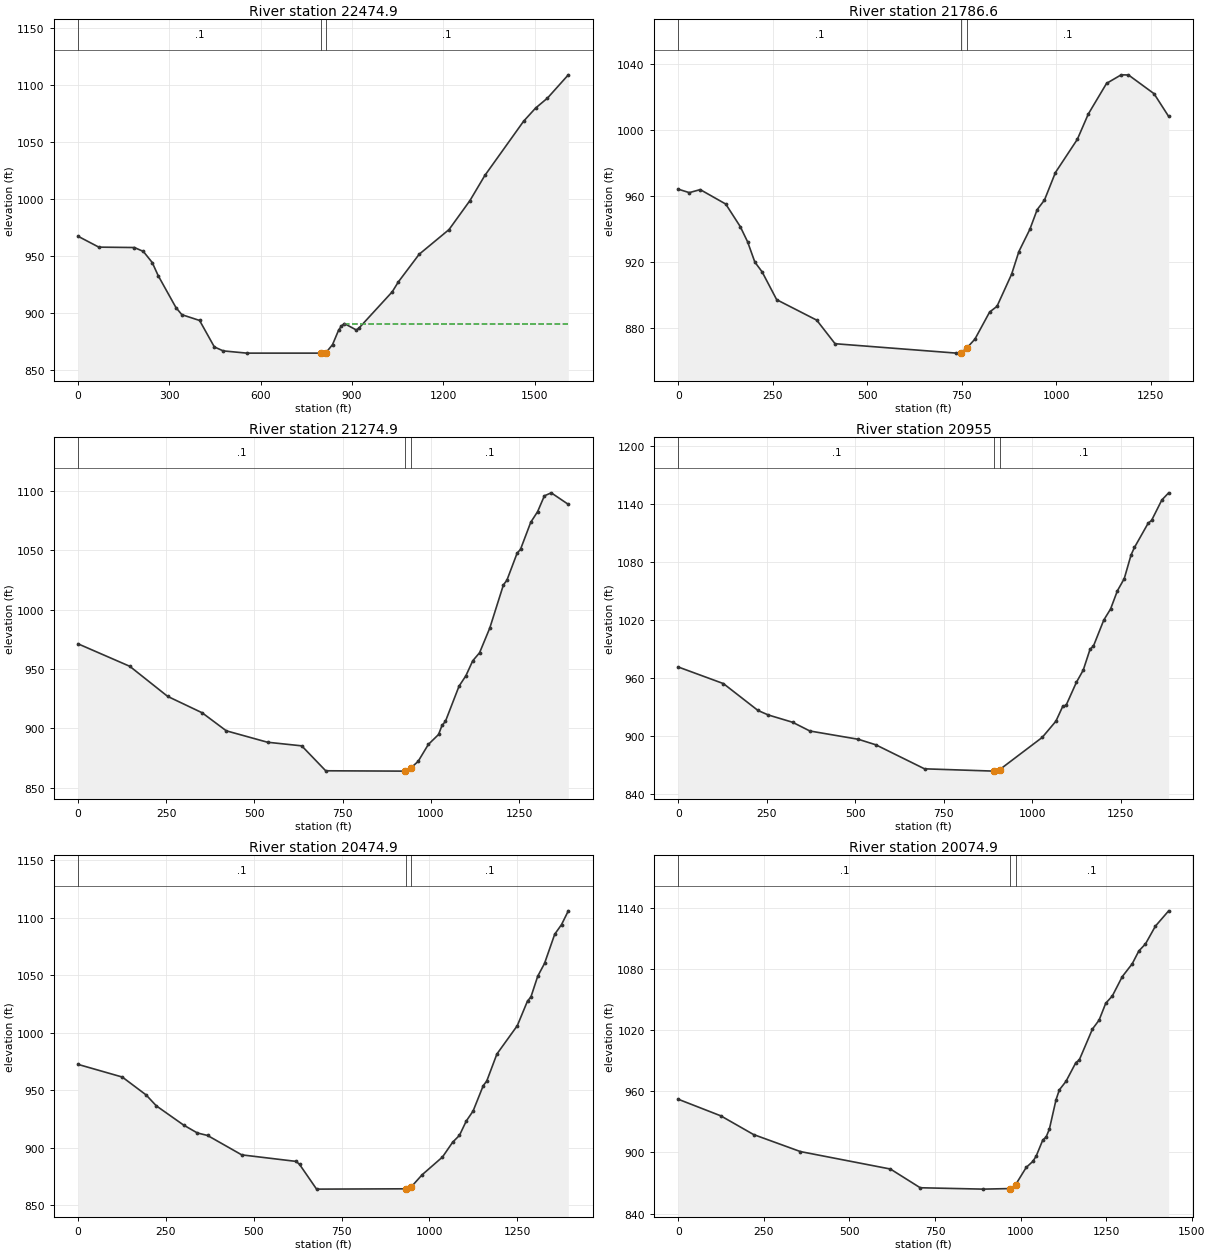
Type RM Length L Ch R = 1 ,22474.9 ,671.863,688.249,703.606
XS GIS Cut Line= 5
     1789578.106      342796.481     1789898.944      342879.632
     1790359.036      342998.873     1790791.123      343129.986
     1791125.646      343241.494
#Sta/Elev= 30
       0  967.22    68.2   957.7   185.2  957.35   214.5  953.93   243.7  944.23
   263.2  932.75   321.7  904.72   341.1   898.5   399.3  893.44   447.8  870.25
   476.9  866.77   554.5  864.81   799.2  864.81   814.2  865.11   836.2  872.28
   855.8  884.75   865.6  888.72   875.4  890.69   914.7  885.04   924.5  887.19
  1032.5   918.6  1052.1  927.11  1120.8  951.45    1219  973.11  1287.7  998.52
  1336.6  1020.5    1464 1068.05  1503.1  1079.5  1542.3 1088.29  1610.9  1108.7
#Mann= 3 , 0 , 0
       0      .1       0   799.2    .045       0   814.2      .1       0
#XS Ineff= 2 , 0
                          875.29          890.74
Permanent Ineff=
       F       F
Bank Sta=799.2,814.2
XS Rating Curve= 0 ,0
Exp/Cntr=0.3,0.1

Type RM Length L Ch R = 1 ,21786.6 ,505.695,511.751,516.4
XS GIS Cut Line= 4
     1789600.838      342917.519     1789812.535      343239.628
     1790064.049      343622.322     1790273.273       344025.78
#Sta/Elev= 30
       0  963.99    28.9  961.94    57.8  963.77   125.3  955.03   163.8  941.35
   183.1   932.2   202.4  919.86   221.6  913.95   260.2  897.09   366.2   884.7
   414.7  870.43   736.2  864.73   748.5  864.98   763.5  867.84   784.9  873.19
   823.9  889.62   843.4  893.07   882.1  912.53   901.4  926.28   930.4  939.71
   949.8  951.65   969.1  957.45   998.1  974.12  1056.1  994.22  1085.1 1009.54
  1133.5 1028.12  1172.2 1033.29  1191.5  1033.2  1259.2 1021.86  1297.9 1008.07
#Mann= 3 , 0 , 0
       0      .1       0   748.5    .045       0   763.5      .1       0
Bank Sta=748.5,763.5
XS Rating Curve= 0 ,0
Exp/Cntr=0.3,0.1

Type RM Length L Ch R = 1 ,21274.9 ,313.758,319.855,327.358
XS GIS Cut Line= 4
     1789274.792      342898.142     1789423.668      343353.186
     1789565.485      343786.657     1789733.614      344209.249
#Sta/Elev= 30
       0  971.13   146.6  952.22     254   926.9   351.8  913.09   420.2  897.92
     537  888.31     634  885.27     702  864.28   925.2  863.99   927.4   864.1
   942.4  866.42   963.9  872.16   992.9  886.45  1021.9  894.82  1031.6  902.43
  1041.3  905.84    1080  935.55  1099.4  944.28  1118.7  956.84  1138.1  963.62
  1167.1  984.44  1205.8 1020.82  1215.5 1024.59  1244.5 1047.42  1254.2  1050.7
  1283.2 1073.45  1302.6 1082.37  1321.9 1095.71  1341.3 1098.23  1389.7 1088.52
#Mann= 3 , 0 , 0
       0      .1       0   927.4    .045       0   942.4      .1       0
Bank Sta=927.4,942.4
XS Rating Curve= 0 ,0
Exp/Cntr=0.3,0.1

Type RM Length L Ch R = 1 ,20955   ,470.496,480.145,489.795
XS GIS Cut Line= 4
     1789211.153      342911.368      1789232.49      343379.994
     1789253.512      343841.683     1789300.594      344292.919
#Sta/Elev= 30
       0  971.39   127.1  954.31   224.8  926.56   254.1  921.89   322.5  914.39
   371.4  905.37   508.4   896.8   557.6  891.13   695.3  866.31   891.9  863.93
   892.9  863.97   907.9  865.58  1027.8  898.75  1066.4  915.46  1085.7  930.76
  1095.4  932.04  1124.3  955.61  1143.6  968.18  1162.9  989.75  1172.6  993.16
  1201.6 1019.84  1220.9 1031.34  1240.2 1050.18  1259.5 1062.66  1278.8 1087.22
  1288.4 1094.92    1327 1119.89  1336.7 1122.79  1365.7 1143.91    1385 1151.27
#Mann= 3 , 0 , 0
       0      .1       0   892.9    .045       0   907.9      .1       0
Bank Sta=892.9,907.9
XS Rating Curve= 0 ,0
Exp/Cntr=0.3,0.1

Type RM Length L Ch R = 1 ,20474.9 ,395.454,400,404.546
XS GIS Cut Line= 5
     1789140.461       342854.99     1789066.323      343044.396
     1788963.597      343306.838     1788797.752      343730.537
     1788631.907      344154.235
#Sta/Elev= 30
       0   972.4   125.9   961.4   193.7  945.86   222.8  936.36   300.6  919.63
   339.5  912.81   368.6  910.63   465.8  893.78   620.8  888.09   630.4  885.45
   678.8     864   932.7  864.28   947.7  865.79     979  876.43    1037  891.88
  1066.1  904.79  1085.4  910.74  1104.8   923.2  1124.2  931.88  1153.2  954.02
  1162.9   957.8  1191.9  981.39    1250 1006.05  1279.1 1027.53  1288.7 1030.96
  1308.1 1049.02  1327.5 1060.16  1356.5 1085.53  1375.9 1093.92  1395.2 1105.86
#Mann= 3 , 0 , 0
       0      .1       0   932.7    .045       0   947.7      .1       0
Bank Sta=932.7,947.7
XS Rating Curve= 0 ,0
Exp/Cntr=0.3,0.1

Type RM Length L Ch R = 1 ,20074.9 ,397.472,400,402.91
XS GIS Cut Line= 5
     1788961.396      342756.793     1788852.779      342924.957
     1788677.767      343195.915       1788430.9      343578.121
     1788184.034      343960.328
#Sta/Elev= 30
       0   952.2   123.9  935.97   219.7   917.6   356.6  900.88   619.6  883.74
   706.7  865.36   890.6  864.01   970.3  864.57   985.3  868.28  1016.5  885.34
  1035.8  891.24  1045.5  896.35  1064.9  912.24  1074.6  915.16  1084.2     923
  1103.6  951.76  1113.3  961.48  1132.6  969.77  1161.7  988.33  1171.4  990.73
  1210.1 1021.23  1229.5 1029.98  1248.8 1046.46  1268.2 1053.72  1297.2 1072.67
  1326.3 1085.27  1345.6 1097.86    1365 1104.76    1394 1122.21  1432.8 1137.26
#Mann= 3 , 0 , 0
       0      .1       0   970.3    .045       0   985.3      .1       0
Bank Sta=970.3,985.3
XS Rating Curve= 0 ,0
Exp/Cntr=0.3,0.1

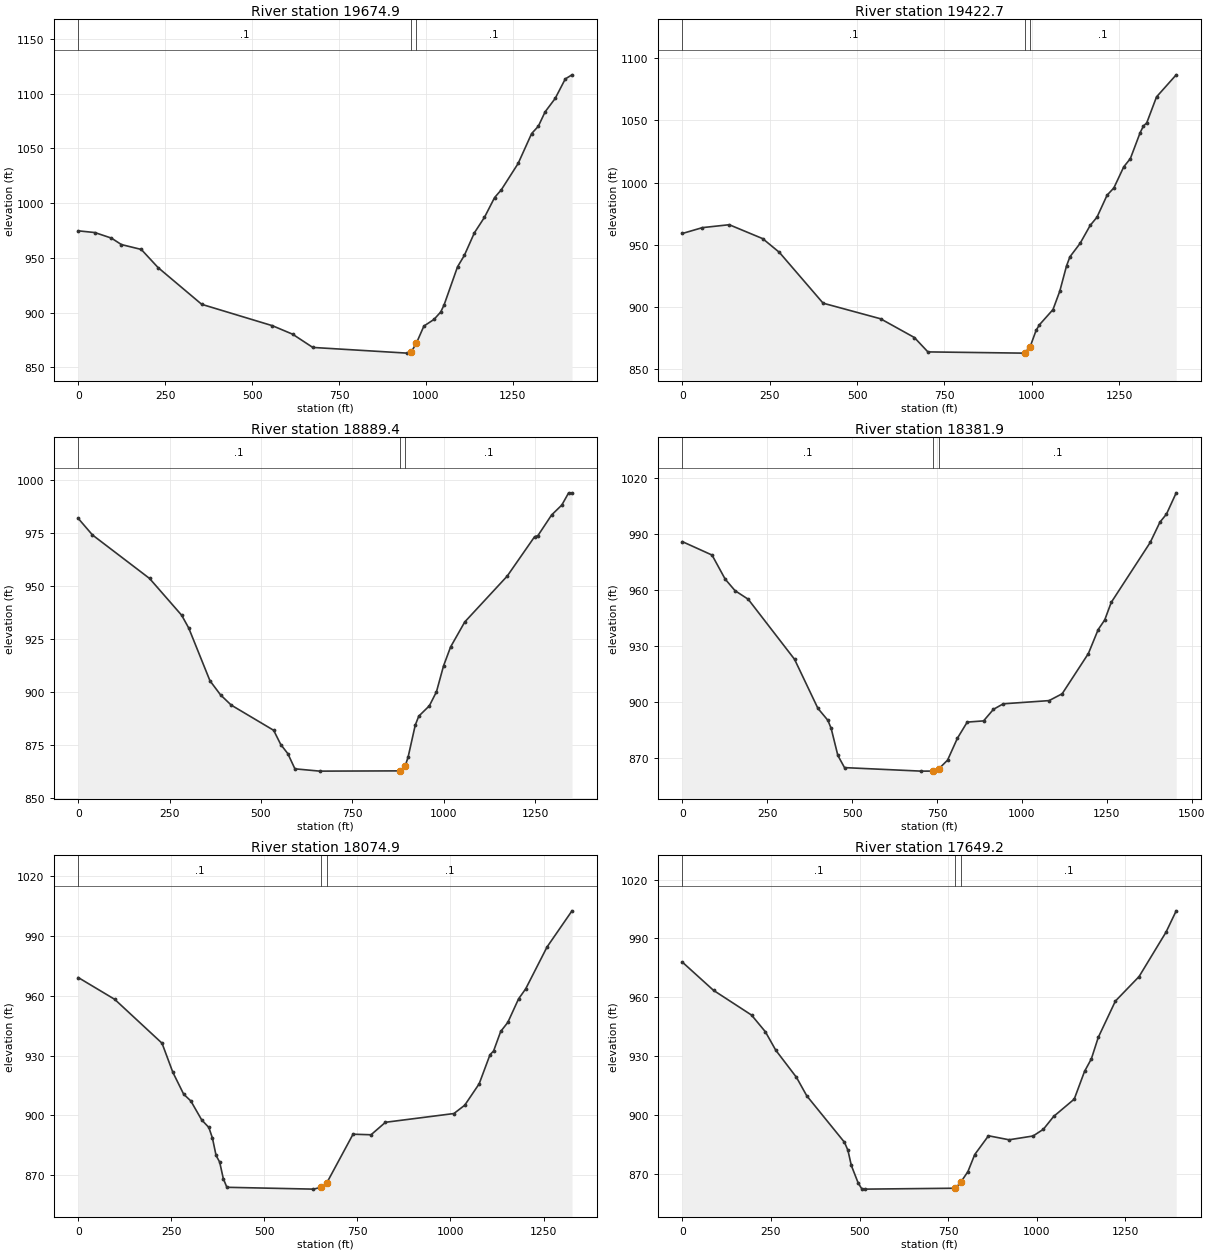
Type RM Length L Ch R = 1 ,19674.9 ,252.491,252.124,251.375
XS GIS Cut Line= 5
     1788704.998      342616.187     1788578.118      342771.333
     1788382.218      343010.873     1788094.121      343363.148
     1787800.149      343710.413
#Sta/Elev= 30
       0  974.66    47.7  973.09    95.4  968.02   124.1  962.12   181.3  957.66
   229.4  941.17   355.1  907.55   558.3  888.03   616.4  880.29   674.5  868.18
   945.6  862.98   957.4  863.91   972.4  872.08     994  887.69    1023  893.75
  1042.4  900.56  1052.1  907.03  1090.8  941.86  1110.2  952.14  1139.2  972.84
  1168.2  987.01  1197.3 1005.02  1216.6 1012.12    1265 1036.16  1303.8 1063.47
  1323.1 1070.16  1342.5 1083.27  1371.5 1095.53  1400.6 1113.37  1419.9 1117.11
#Mann= 3 , 0 , 0
       0      .1       0   957.4    .045       0   972.4      .1       0
Bank Sta=957.4,972.4
XS Rating Curve= 0 ,0
Exp/Cntr=0.3,0.1

Type RM Length L Ch R = 1 ,19422.7 ,535.947,533.305,530.662
XS GIS Cut Line= 5
     1788509.183      342432.072     1788301.318      342694.863
     1788019.047      343051.722     1787736.776       343408.58
     1787632.041      343540.991
#Sta/Elev= 30
       0  959.04    57.4  963.74     134  966.07   229.8  954.88   277.6  943.83
   402.8  902.97   567.4  890.42   664.2  875.35   702.9  863.79     974   862.8
   980.8  863.19   995.8  868.06  1012.7  881.08  1022.4  885.64  1061.1  897.83
  1080.5   912.6  1099.8   932.9  1109.5  940.24  1138.6  951.03  1167.6  965.53
    1187  972.09    1216  989.84  1235.4  995.66  1263.8 1012.66  1282.6 1019.22
  1310.7 1040.14  1320.1 1045.47  1329.5 1047.94  1357.6 1068.89  1413.9 1086.61
#Mann= 3 , 0 , 0
       0      .1       0   980.8    .045       0   995.8      .1       0
Bank Sta=980.8,995.8
XS Rating Curve= 0 ,0
Exp/Cntr=0.3,0.1

Type RM Length L Ch R = 1 ,18889.4 ,508.278,507.532,506.425
XS GIS Cut Line= 5
     1787950.885      342132.353     1787803.411      342362.449
     1787557.842      342745.598     1787319.292       343133.03
     1787231.463      343275.674
#Sta/Elev= 30
       0  981.75      39  973.95   195.2  953.48     283  936.17   302.3  930.16
   360.4  905.34   389.5  898.67   418.5   893.9   534.7  882.02   554.1  875.33
   573.5  871.03   592.8  863.89   660.6  862.81   879.5  862.93   894.5  865.21
   902.6  869.48     922  884.43   931.7  888.68   960.7  893.57   980.1  900.16
   999.4  912.32  1018.8  921.27  1057.5  933.02  1173.7  954.61  1248.5  973.12
  1257.8  973.69  1295.1  983.37    1323  988.03  1341.6  993.74  1350.9  993.79
#Mann= 3 , 0 , 0
       0      .1       0   879.5    .045       0   894.5      .1       0
Bank Sta=879.5,894.5
XS Rating Curve= 0 ,0
Exp/Cntr=0.3,0.1

Type RM Length L Ch R = 1 ,18381.9 ,313.047,307.04,300.773
XS GIS Cut Line= 5
      1787477.75       341951.19     1787334.383      342158.276
     1787081.957      342601.292     1786836.234      343004.988
     1786721.772      343193.036
#Sta/Elev= 30
       0  986.04    87.2  978.85   125.9  965.92     155  959.72   193.7  955.13
   330.3  922.85     399  896.54   428.4  890.11   438.2  885.71   457.8  871.25
   477.4   864.7   702.9  862.81   739.5  862.84   754.5  863.93     781  868.71
     810  880.48   838.9  889.14   887.1  889.79   916.1  895.99     945  898.96
    1080  900.68  1118.6  904.36  1195.8  925.96  1224.7  938.85  1243.9  943.99
  1263.1  953.42  1377.9  985.61  1406.6  996.53  1425.8 1000.83  1454.5 1012.27
#Mann= 3 , 0 , 0
       0      .1       0   739.5    .045       0   754.5      .1       0
Bank Sta=739.5,754.5
XS Rating Curve= 0 ,0
Exp/Cntr=0.3,0.1

Type RM Length L Ch R = 1 ,18074.9 ,421.424,425.686,430.591
XS GIS Cut Line= 5
     1786965.673      341855.587     1786913.341      342054.552
     1786797.604      342494.586     1786681.867       342934.62
     1786628.275      343138.378
#Sta/Elev= 30
       0   969.2      98  958.24   225.1  936.19   254.1   921.6   283.2  910.59
   302.5  907.16   331.6  897.66   350.9  893.84   360.6  888.46   370.3  879.78
     380  876.43   389.7  868.14   399.3  863.78   631.7  862.86   653.2  863.79
   668.2  866.17   738.2  890.46   786.6  890.18   825.3  896.45  1009.2  900.85
  1038.3  905.04    1077  915.78  1106.1  930.39  1115.7  932.27  1134.9  942.11
    1154  946.66  1182.8  958.45  1201.9  963.49  1259.4  984.56  1326.4 1002.72
#Mann= 3 , 0 , 0
       0      .1       0   653.2    .045       0   668.2      .1       0
Bank Sta=653.2,668.2
XS Rating Curve= 0 ,0
Exp/Cntr=0.3,0.1

Type RM Length L Ch R = 1 ,17649.2 ,412.944,413.581,414.824
XS GIS Cut Line= 5
     1786708.276      341702.246     1786572.883      341994.353
     1786381.557      342407.132      1786178.97       342814.77
     1786106.903      342959.781
#Sta/Elev= 30
       0  977.94    87.8  963.62   195.1  951.05   234.2  942.55   263.4  933.21
     322  919.36     351  909.99   457.5  886.34   467.2  882.29   476.8  874.58
   496.2  865.62   505.9  862.79   515.6  862.51   770.8  862.97   785.8  866.03
     806  871.41   825.3   880.1   864.1  889.65   922.2  887.61     990  889.54
  1019.1  892.96  1048.1  899.48  1106.2  908.29  1135.3  922.39  1154.6   928.8
    1174  939.67  1222.4  958.16  1289.3  970.64  1365.5  993.27  1394.1 1004.07
#Mann= 3 , 0 , 0
       0      .1       0   770.8    .045       0   785.8      .1       0
Bank Sta=770.8,785.8
XS Rating Curve= 0 ,0
Exp/Cntr=0.3,0.1

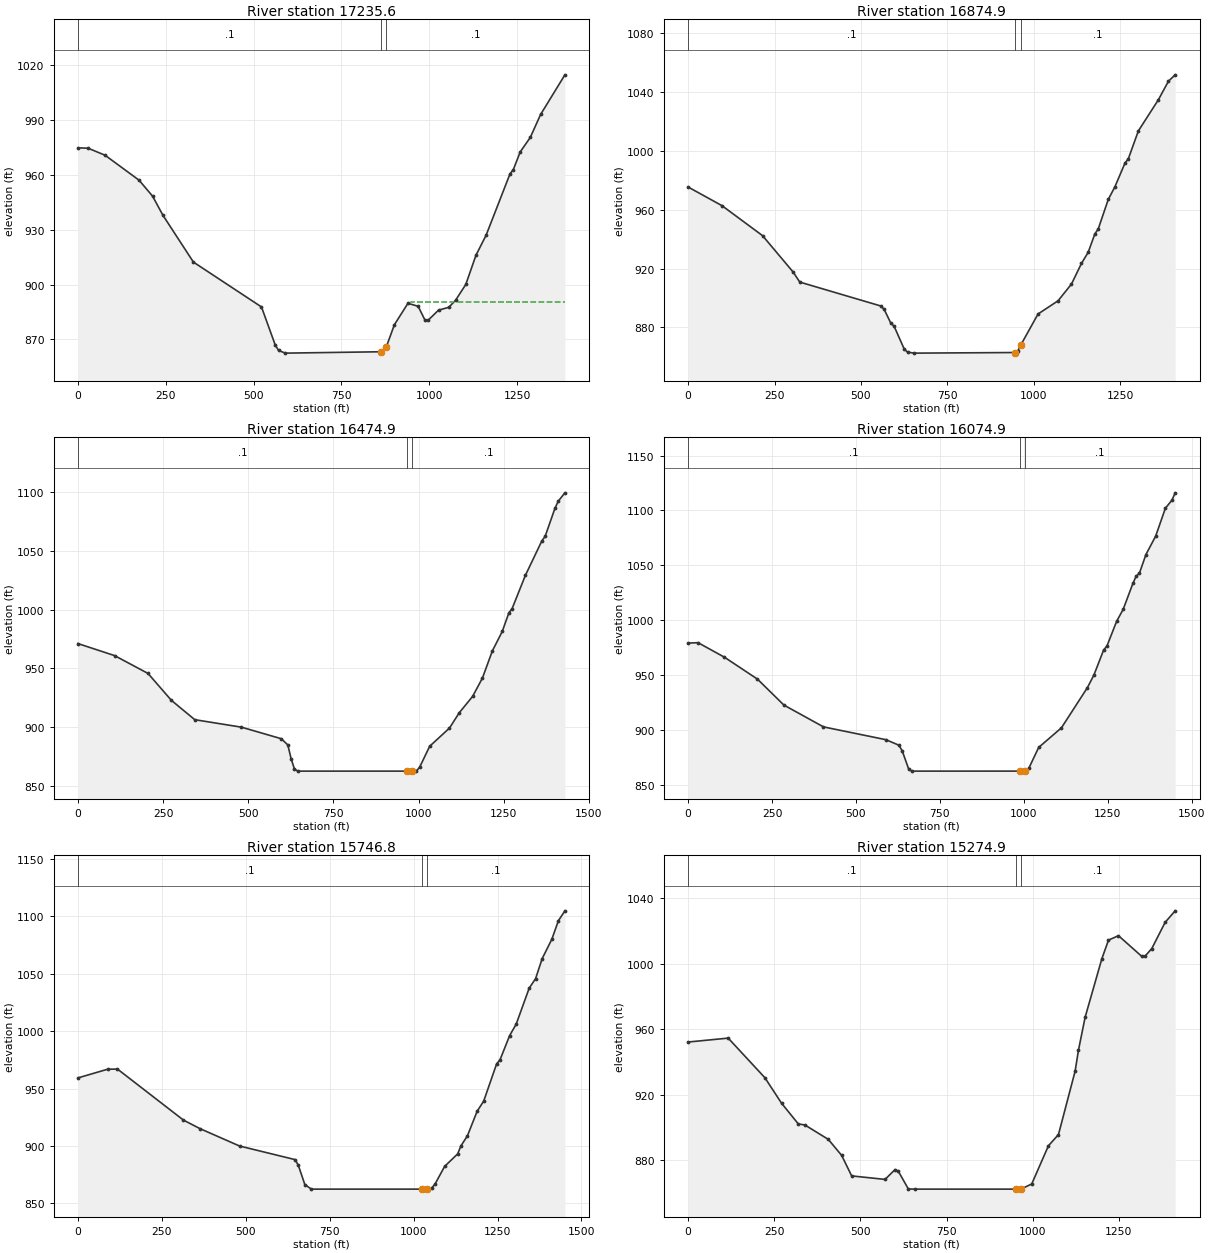
Type RM Length L Ch R = 1 ,17235.6 ,362.833,360.732,357.009
XS GIS Cut Line= 5
     1786369.467      341572.257     1786180.051      341942.439
     1785972.396      342348.264     1785742.873      342740.954
     1785712.844      342792.331
#Sta/Elev= 30
       0  974.83      29  974.64    77.4  970.78   174.1  957.13   212.7  948.37
   241.8     938   328.8  912.32   522.5  887.78   561.3  867.15     571  864.01
   590.4  862.51   863.1  863.26   878.1  866.07   900.7  878.01   939.4  889.78
   968.5  888.12   987.8  880.57   997.5  880.63  1026.5  886.04  1055.6  887.58
  1074.9  891.44    1104  900.08    1133  916.08    1162   927.1  1229.8  960.59
  1239.4  962.98  1258.8  972.56  1287.8   980.6  1316.9  993.08  1386.1 1014.78
#Mann= 3 , 0 , 0
       0      .1       0   863.1    .045       0   878.1      .1       0
#XS Ineff= 2 , 0
                          947.39          890.25
Permanent Ineff=
       F       F
Bank Sta=863.1,878.1
XS Rating Curve= 0 ,0
Exp/Cntr=0.3,0.1

Type RM Length L Ch R = 1 ,16874.9 ,395.5,400,404.874
XS GIS Cut Line= 4
     1785980.953      341365.447      1785795.37      341828.975
     1785626.224      342251.449     1785464.165      342676.596
#Sta/Elev= 30
       0  975.42    97.9  962.75   215.4  942.35   303.5  917.72   323.1   910.8
   557.4  894.56   567.1   892.3   586.4  882.95   596.1  880.76   625.2   865.3
   634.9  863.16   654.2  862.51   946.9  862.92   954.4  864.15   961.9  867.72
  1012.5  889.11  1070.5  898.08  1109.3  909.47  1138.3  923.52  1157.7  931.05
    1177  943.56  1186.7   946.9  1215.8  966.99  1235.1  975.62  1264.2  991.74
  1273.8  994.59  1302.9 1013.58    1361 1034.81    1390 1047.38  1409.4 1051.69
#Mann= 3 , 0 , 0
       0      .1       0   946.9    .045       0   961.9      .1       0
Bank Sta=946.9,961.9
XS Rating Curve= 0 ,0
Exp/Cntr=0.3,0.1

Type RM Length L Ch R = 1 ,16474.9 ,399.597,400,400.403
XS GIS Cut Line= 4
     1785810.177      341246.226     1785525.343      341680.475
     1785275.792      342060.935     1785026.241      342441.394
#Sta/Elev= 30
       0   971.1   107.8  960.83   205.8  945.66   274.4  922.76     343   906.3
   480.1  899.92   596.8   890.1   616.1  884.84   625.8  873.05   635.5  864.31
   645.2  862.51   966.8  862.51   981.8  862.53   993.7  862.61  1003.4   866.1
  1032.4  883.66  1090.5  899.15  1119.5   912.3  1158.3  926.06  1187.3  941.74
  1216.4  964.84  1245.4  981.37  1264.8   997.2  1274.4 1000.89  1313.2 1029.08
  1361.6 1058.46  1371.2 1062.29  1400.3 1086.39    1410 1092.38  1429.3  1099.4
#Mann= 3 , 0 , 0
       0      .1       0   966.8    .045       0   981.8      .1       0
Bank Sta=966.8,981.8
XS Rating Curve= 0 ,0
Exp/Cntr=0.3,0.1

Type RM Length L Ch R = 1 ,16074.9 ,326.231,328.092,329.953
XS GIS Cut Line= 4
     1785504.553      341015.425     1785199.851      341462.316
      1784943.53      341838.248      1784687.21       342214.18
#Sta/Elev= 30
       0  979.12    29.5  979.49   108.2  966.24   206.5  946.29   285.2  922.67
   403.2  902.79   589.3  891.12     628  886.08   637.7  880.98   657.1  864.27
   666.7  862.49   988.4  862.51  1003.4  862.62  1015.2   865.3  1044.3  884.09
  1112.1  901.95  1189.5  938.57  1208.9   950.1  1237.9  972.92  1247.6  976.42
  1276.6  999.04    1296 1009.85    1325  1033.5  1334.7 1040.04  1344.4 1042.79
  1363.8 1059.78  1392.8 1076.56  1421.8 1102.02  1441.2 1109.27  1450.9    1116
#Mann= 3 , 0 , 0
       0      .1       0   988.4    .045       0  1003.4      .1       0
Bank Sta=988.4,1003.4
XS Rating Curve= 0 ,0
Exp/Cntr=0.3,0.1

Type RM Length L Ch R = 1 ,15746.8 ,469.799,471.908,474.017
XS GIS Cut Line= 4
     1785362.238      340855.772     1785007.573      341263.622
     1784708.786      341607.212     1784422.336      341960.649
#Sta/Elev= 30
       0  959.32    88.4  966.89   117.9  967.03   314.5   922.6   363.6   915.2
   481.5  900.05   647.1   888.2   656.7  883.22   676.1  866.47   695.5  862.51
  1026.1  862.51  1041.1  862.72  1053.9  863.48  1063.6  866.78  1092.6  882.35
  1131.3  893.17    1141  900.13  1160.4  908.92  1189.4  930.36  1208.8  939.08
  1247.5  971.67  1257.2  974.85  1286.2  996.23  1305.6 1006.09  1344.3  1037.4
  1363.6 1045.88    1383 1063.14    1412 1080.16  1431.4  1096.2  1450.8  1104.8
#Mann= 3 , 0 , 0
       0      .1       0  1026.1    .045       0  1041.1      .1       0
Bank Sta=1026.1,1041.1
XS Rating Curve= 0 ,0
Exp/Cntr=0.3,0.1

Type RM Length L Ch R = 1 ,15274.9 ,399.525,400,400.475
XS GIS Cut Line= 4
     1785013.462       340626.95     1784661.105       340986.88
      1784342.81      341312.017     1784024.516      341637.153
#Sta/Elev= 30
       0  952.25   116.2  954.64   222.8  930.46   271.2   914.9   319.7   902.3
     339  901.63   406.8  892.87   445.6  883.09   474.6  870.58   571.5  868.44
   600.5  874.44   610.2  873.38   639.2  862.59   658.6  862.51   951.2  862.51
   966.2  862.51   997.4  865.69  1045.8  888.96  1074.9  895.78  1123.3  934.49
  1132.9  947.18  1152.3  967.36  1200.7 1002.95  1220.1 1014.41  1249.1 1017.13
  1316.9 1004.48  1326.6 1004.71  1345.9  1009.3  1384.6 1025.28  1413.7 1032.29
#Mann= 3 , 0 , 0
       0      .1       0   951.2    .045       0   966.2      .1       0
Bank Sta=951.2,966.2
XS Rating Curve= 0 ,0
Exp/Cntr=0.3,0.1

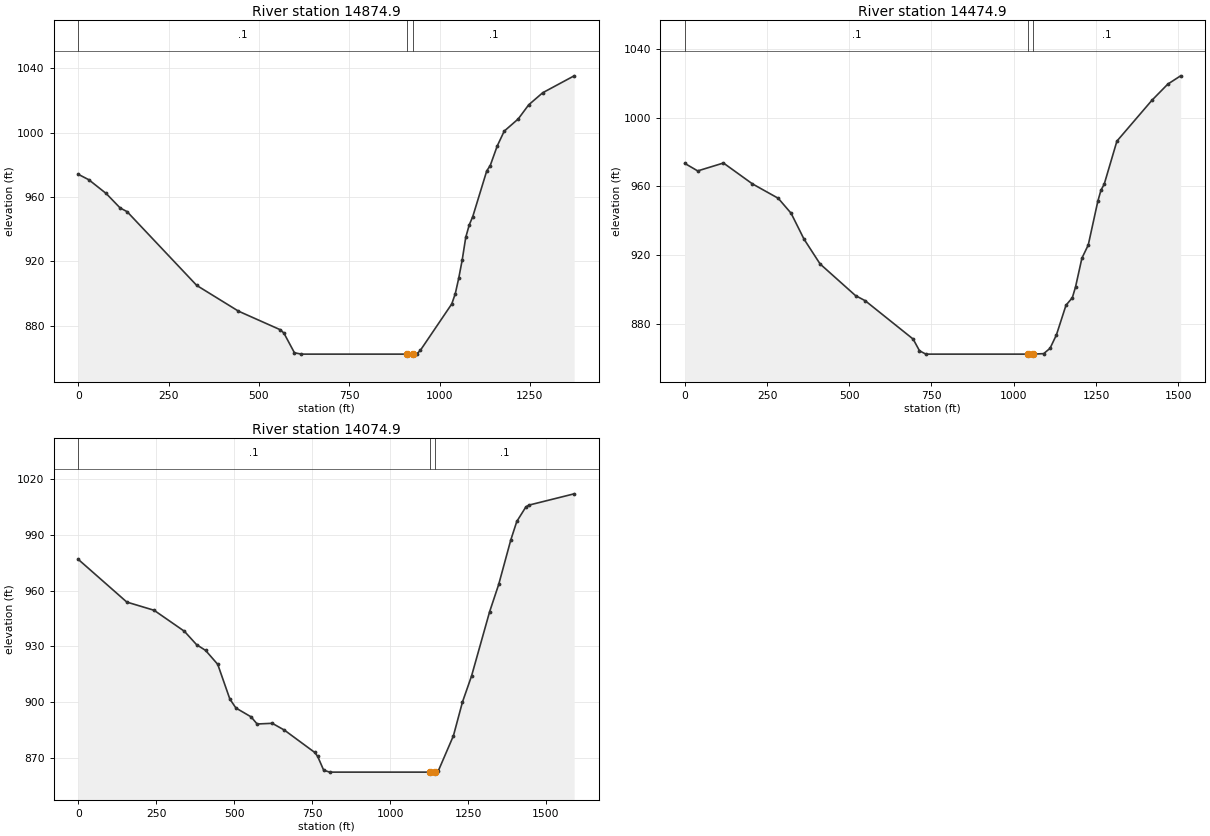
Type RM Length L Ch R = 1 ,14874.9 ,401.431,400,398.568
XS GIS Cut Line= 4
      1784713.27      340389.485     1784382.666      340713.238
     1784057.582      341031.586     1783732.498      341349.934
#Sta/Elev= 30
       0  974.07    28.9  970.73    77.1  962.18   115.7  953.21     135  950.91
   327.8  905.14   443.4  889.17   559.5   877.6   569.2  875.52   598.3  863.35
   617.6  862.51   910.2  862.51   925.2  862.52   937.1  862.66   946.8  864.82
  1033.9  893.67  1043.6  900.01  1053.3  909.79  1062.9  921.11  1072.6  935.02
  1082.3  942.72    1092  947.87  1130.7  976.21  1140.4  979.54  1159.7  991.66
  1179.1 1000.88  1217.8 1008.43  1246.9 1017.21  1285.6 1024.69  1372.7 1035.19
#Mann= 3 , 0 , 0
       0      .1       0   910.2    .045       0   925.2      .1       0
Bank Sta=910.2,925.2
XS Rating Curve= 0 ,0
Exp/Cntr=0.3,0.1

Type RM Length L Ch R = 1 ,14474.9 ,399.801,400,400.199
XS GIS Cut Line= 4
     1784476.823      339967.855     1784077.449       340412.09
     1783773.255      340750.455     1783469.061       341088.82
#Sta/Elev= 30
       0   973.4    39.2  969.03   117.5  973.62   205.7  961.48     284  953.13
   323.2  944.41   362.3  929.42   411.3  914.94     519  896.54   548.4  893.57
   694.2  871.26   713.5  864.47   732.9  862.51  1044.9  862.51  1059.9  862.51
  1091.1   862.8  1110.4   865.9  1129.8  873.69  1158.9  890.94  1178.2  895.32
  1187.9  901.57  1207.3  918.31  1226.6  925.96  1255.7  951.41  1265.3  957.87
    1275  961.26  1313.7  986.35  1420.2 1010.11  1468.6 1019.52  1507.4 1024.31
#Mann= 3 , 0 , 0
       0      .1       0  1044.9    .045       0  1059.9      .1       0
Bank Sta=1044.9,1059.9
XS Rating Curve= 0 ,0
Exp/Cntr=0.3,0.1

Type RM Length L Ch R = 1 ,14074.9 ,309.06,309.181,309.303
XS GIS Cut Line= 4
     1784243.451      339644.146     1783784.072      340146.141
     1783476.902      340481.807     1783169.732      340817.473
#Sta/Elev= 30
       0   976.7   155.5  953.81     243   949.4   340.2  938.13   379.1  930.98
   408.3  927.84   447.2  920.37     486  901.76   505.5  896.93   554.1  892.19
   573.5  888.35   622.1  888.72     661  885.07   757.9  873.13   767.6     871
     787  863.55   806.3  862.51    1128  862.51    1143  862.53  1154.8  863.21
  1203.2  882.03  1232.3  900.19  1261.3  914.09  1319.4  948.67  1348.4  963.26
  1387.2  987.13  1406.5   997.1  1435.6 1004.89  1445.2 1005.85  1590.5 1011.92
#Mann= 3 , 0 , 0
       0      .1       0    1128    .045       0    1143      .1       0
Bank Sta=1128,1143
XS Rating Curve= 0 ,0
Exp/Cntr=0.3,0.1