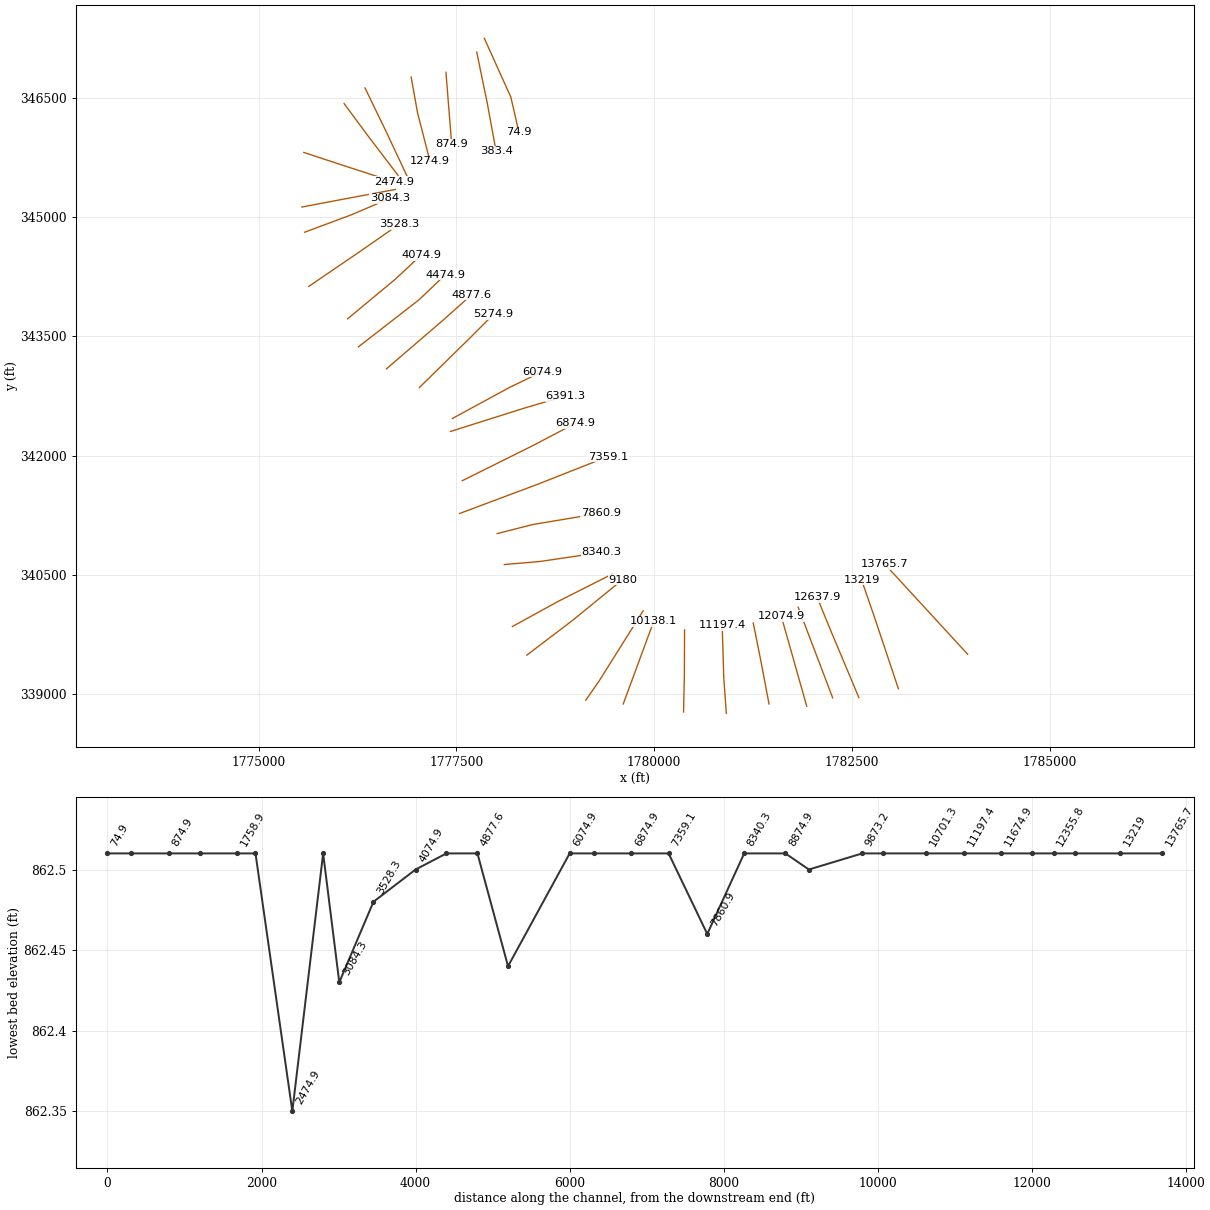
HEC-RAS study TygrtVlyRv.prj: TygrtVlyRv

--- TygrtVlyRv.g01 (geometry) --- (continued)

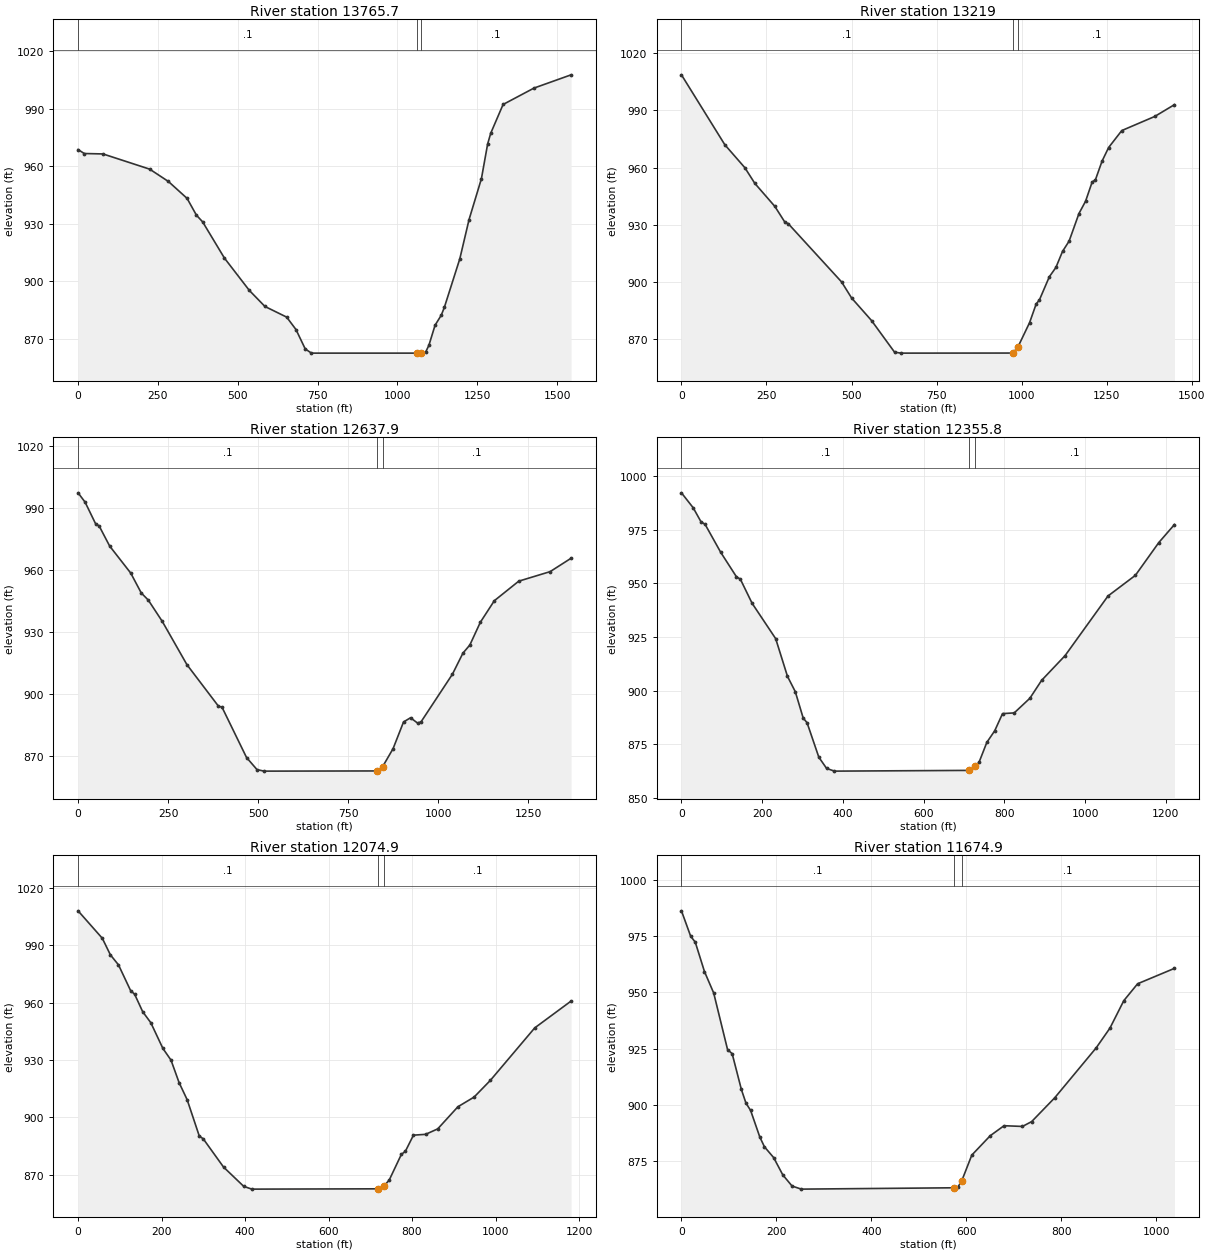
Type RM Length L Ch R = 1 ,13765.7 ,556.208,546.68,537.269
XS GIS Cut Line= 4
     1783965.033      339499.041      1783534.88      339964.759
     1783226.162      340299.002     1782917.445      340633.245
#Sta/Elev= 30
       0  968.73    19.5  966.69      78  966.47   224.3  958.53   282.9   952.1
   341.4  943.28   370.6  934.53   390.1  931.02   458.4  912.11   536.4  895.23
   585.2  886.87   653.3   881.3   682.4  874.83   711.4  864.71   730.8  862.51
  1059.9  862.51  1074.9  862.53    1089  863.22  1098.7  866.59    1118  877.08
  1137.4  882.29  1147.1  886.39  1195.5  911.74  1224.5  932.25  1263.2  953.57
  1282.6  971.63  1292.3  977.26    1331  992.28  1427.8 1000.84    1544 1007.76
#Mann= 3 , 0 , 0
       0      .1       0  1059.9    .045       0  1074.9      .1       0
Bank Sta=1059.9,1074.9
XS Rating Curve= 0 ,0
Exp/Cntr=0.3,0.1

Type RM Length L Ch R = 1 ,13219   ,579.418,581.118,582.702
XS GIS Cut Line= 4
     1783089.625      339064.223     1782917.705       339575.57
     1782772.711      340006.831     1782623.003      340436.543
#Sta/Elev= 30
       0 1008.71   127.5  971.99   186.4  959.92   215.8  951.67   274.6  939.59
   304.1   931.3   313.9  930.53   470.8  899.91   500.2  891.49   558.8  879.64
   626.6  862.99     646  862.51   974.8  862.55   989.8  865.94  1023.5  878.52
  1042.9  888.33  1052.5   890.5  1081.6  902.63    1101  907.54  1120.3  915.92
  1139.7  921.35  1168.7  935.86  1188.1   942.3  1207.5  952.41  1217.1  953.56
  1236.5  963.34  1255.9  970.52  1294.6  979.43  1391.4  986.83  1449.5  993.05
#Mann= 3 , 0 , 0
       0      .1       0   974.8    .045       0   989.8      .1       0
Bank Sta=974.8,989.8
XS Rating Curve= 0 ,0
Exp/Cntr=0.3,0.1

Type RM Length L Ch R = 1 ,12637.9 ,282.818,282.061,281.304
XS GIS Cut Line= 4
     1782589.314       338953.22     1782411.521      339375.292
     1782234.797      339794.826     1782060.973      340215.756
#Sta/Elev= 30
       0  997.44    19.5  992.92    48.7  982.43    58.5  981.39    87.7  971.63
   146.2  958.53   175.4   948.9   194.9  945.44   233.9  935.07   302.1  914.15
   389.8  893.97   399.5  893.53   467.7   869.1   496.7  863.25   516.1  862.51
   830.4   862.6   845.4  864.67   874.5  873.43   903.5  886.35   922.9  888.38
   942.3  885.83     952  886.38  1039.2   909.5  1068.3   919.7  1087.6  923.67
  1116.7  934.69  1155.5  945.13  1223.3  954.61  1310.5  959.24  1368.6  965.73
#Mann= 3 , 0 , 0
       0      .1       0   830.4    .045       0   845.4      .1       0
Bank Sta=830.4,845.4
XS Rating Curve= 0 ,0
Exp/Cntr=0.3,0.1

Type RM Length L Ch R = 1 ,12355.8 ,282.948,280.959,278.971
XS GIS Cut Line= 4
     1782258.253      338950.429     1782147.152      339241.148
     1781984.726      339666.168     1781822.299      340091.189
#Sta/Elev= 30
       0  992.18    29.2  985.18    48.6  978.63    58.4  977.55    97.3  964.45
   136.2  953.07   145.9  951.95   175.1  940.68   233.4  924.24   262.6  906.68
     282  899.52   301.5  887.27   311.2  885.03   340.3  868.99   359.6  863.76
     379  862.51   713.2  862.85   728.2  864.79   737.2  866.66   756.5  875.93
   775.9  881.29   795.3   889.3   824.3  889.64     863  896.45   892.1   904.8
   950.2  916.32  1056.6  944.12  1124.4  953.74  1182.5  969.03  1221.2  977.41
#Mann= 3 , 0 , 0
       0      .1       0   713.2    .045       0   728.2      .1       0
Bank Sta=713.2,728.2
XS Rating Curve= 0 ,0
Exp/Cntr=0.3,0.1

Type RM Length L Ch R = 1 ,12074.9 ,401.981,400,398.253
XS GIS Cut Line= 4
     1781930.146      338844.935      1781856.12      339105.616
     1781731.827       339543.31     1781607.534      339981.004
#Sta/Elev= 30
       0 1008.09    58.1  993.72    77.4  985.07    96.8  979.83   125.8  966.39
   135.5  964.46   154.8  955.32   174.2  949.58   203.2   936.1   222.6  930.01
     242  918.22   261.3  909.29   290.3  890.32     300  888.79   348.4  874.07
   396.8  863.96   416.2  862.51   718.5  862.67   733.5  864.34   745.3  867.24
   774.4  880.66   784.1  882.33   803.4  890.74   832.5  891.17   861.5  894.02
   909.9   905.6   948.6  910.65   987.4  919.35  1093.9  946.85    1181  960.89
#Mann= 3 , 0 , 0
       0      .1       0   718.5    .045       0   733.5      .1       0
Bank Sta=718.5,733.5
XS Rating Curve= 0 ,0
Exp/Cntr=0.3,0.1

Type RM Length L Ch R = 1 ,11674.9 ,481.015,477.428,473.605
XS GIS Cut Line= 3
     1781453.601      338872.784     1781344.329      339444.771
     1781254.128      339891.669
#Sta/Elev= 30
       0  986.28    19.4  974.99    29.1  972.34    48.5  959.25    67.9  949.73
    97.1  924.57   106.8  922.74   126.2  906.83   135.9  900.73   145.6  897.53
     165  885.69   174.7  881.35   194.1  876.55   213.5  868.81   232.9  863.89
   252.3  862.51   574.8  863.11   582.3  863.55   589.8  865.95   611.4  877.64
   650.2  886.26   679.3  890.71   718.1  890.39   737.5  892.55     786  903.12
   873.3  925.33   902.4  934.15   931.5  946.33   960.6  953.84  1038.2   960.7
#Mann= 3 , 0 , 0
       0      .1       0   574.8    .045       0   589.8      .1       0
Bank Sta=574.8,589.8
XS Rating Curve= 0 ,0
Exp/Cntr=0.3,0.1

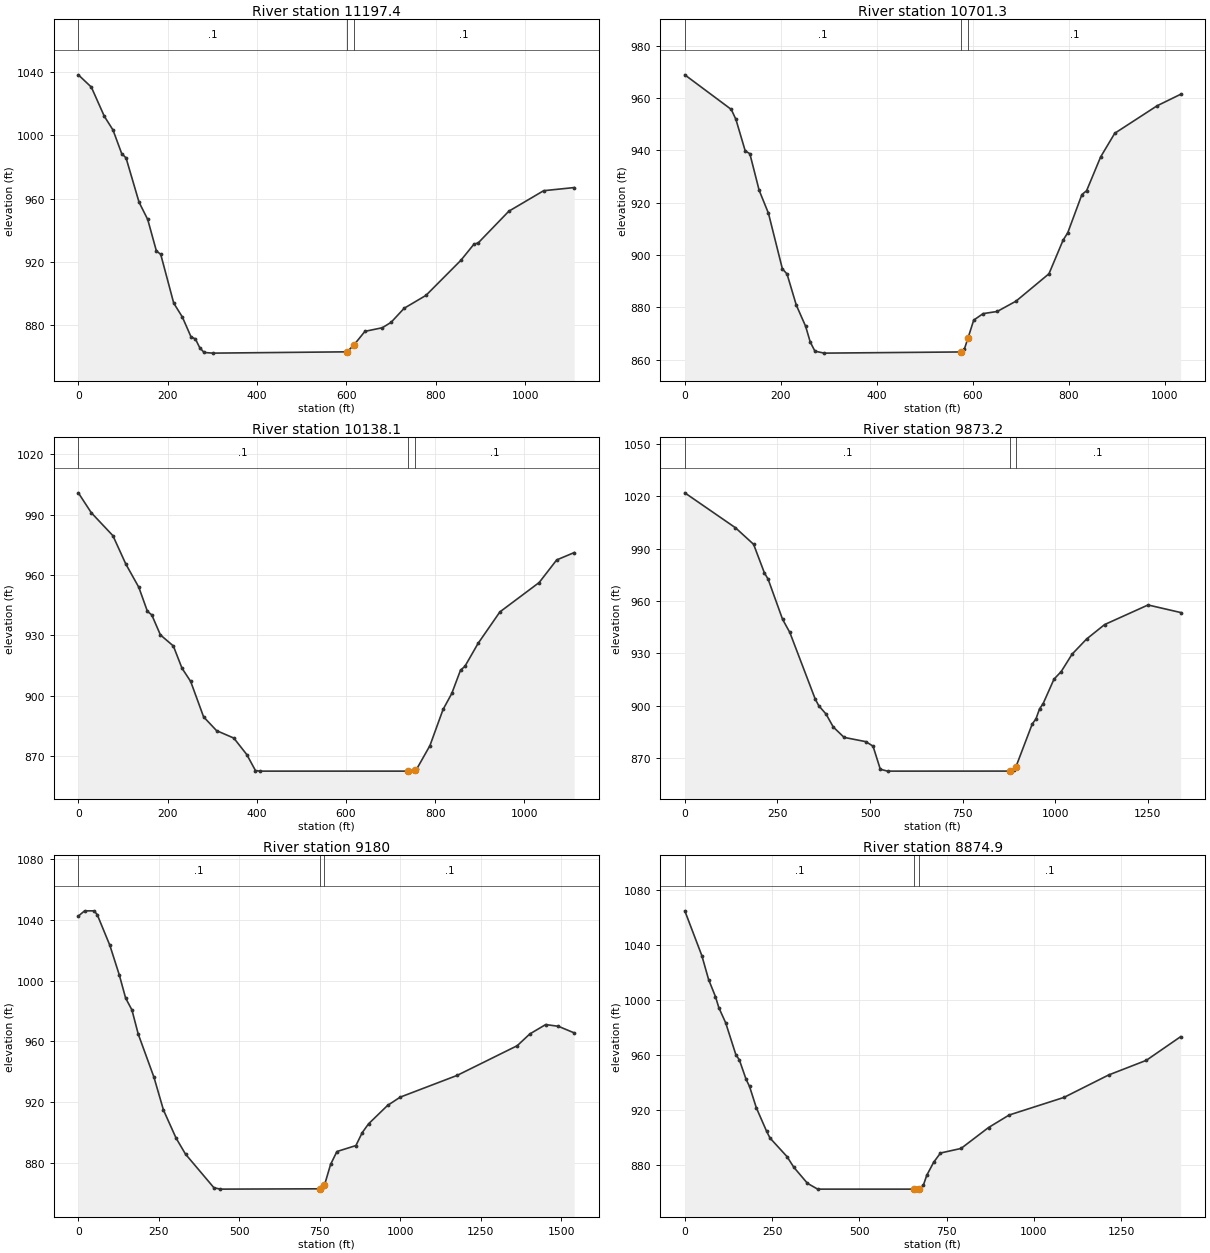
Type RM Length L Ch R = 1 ,11197.4 ,496.871,496.094,495.317
XS GIS Cut Line= 3
     1780913.274      338754.651     1780880.994      339209.637
     1780861.281      339863.008
#Sta/Elev= 30
       0 1038.13    29.1 1030.38    58.2 1011.96    77.6  1003.3      97  988.48
   106.8   985.7   135.9  957.75   155.3  946.85   174.7  926.99   184.4  924.86
   213.5  894.07   232.9  885.25   252.3  872.73     262  871.47   271.7  865.97
   281.4  862.93   300.9  862.51   601.5  863.33   616.5  867.54   641.5  876.25
   680.5  878.54     700  881.94   729.3  890.82   778.1  898.95   856.1  921.04
   885.4  931.22   895.2  932.11   963.5  952.05  1041.5  965.01  1109.8  966.99
#Mann= 3 , 0 , 0
       0      .1       0   601.5    .045       0   616.5      .1       0
Bank Sta=601.5,616.5
XS Rating Curve= 0 ,0
Exp/Cntr=0.3,0.1

Type RM Length L Ch R = 1 ,10701.3 ,571.162,563.262,555.362
XS GIS Cut Line= 3
     1780372.547      338772.491     1780382.969      339227.372
     1780385.611      339805.351
#Sta/Elev= 30
       0  968.87    96.8  955.65   106.5  951.83   125.9  939.79   135.5  938.73
   154.9  924.75   174.3  915.95   203.3  894.72     213  892.75   232.3  880.86
   251.7  872.78   261.4  866.74   271.1  863.26   290.4  862.51   575.2  862.96
   582.4  864.03   590.2  868.37   601.9  875.12   621.5  877.61   650.9  878.43
   690.1  882.38   758.7  892.84   788.1  905.67   797.9  908.54   827.3   923.1
   837.1  924.58   866.4  937.51   895.8  946.54     984  957.04    1033  961.43
#Mann= 3 , 0 , 0
       0      .1       0   575.2    .045       0   590.2      .1       0
Bank Sta=575.2,590.2
XS Rating Curve= 0 ,0
Exp/Cntr=0.3,0.1

Type RM Length L Ch R = 1 ,10138.1 ,269.628,264.821,260.015
XS GIS Cut Line= 3
     1779610.261      338873.588     1779768.346      339300.394
     1779996.426       339915.86
#Sta/Elev= 30
       0 1000.81    29.1  990.91    77.5  979.52   106.5   965.4   135.6  953.86
   154.9  941.89   164.6  940.16     184   930.2     213  924.71   232.4  913.65
   251.8  907.09   280.8  889.47   309.9  882.63   348.6  878.93   377.7  870.71
     397  862.82   406.7  862.51   739.2  862.51   754.2  863.12   758.8  863.66
   788.2   875.2   817.6  893.15   837.2  901.13   856.8  912.71   866.6  914.58
     896  925.95     945  941.63  1033.1  956.24  1072.3  967.46  1111.5  971.11
#Mann= 3 , 0 , 0
       0      .1       0   739.2    .045       0   754.2      .1       0
Bank Sta=739.2,754.2
XS Rating Curve= 0 ,0
Exp/Cntr=0.3,0.1

Type RM Length L Ch R = 1 ,9873.2  ,701.054,693.212,685.37
XS GIS Cut Line= 3
     1779136.376      338921.276     1779304.542      339161.514
     1779861.893      340045.588
#Sta/Elev= 30
       0 1021.96   136.8 1001.94   185.7  992.46     215  976.01   224.8  972.55
   263.9   949.5   283.5  941.95   351.9  903.86   361.6  899.99   381.2  895.23
   400.7   887.8     430  881.84   488.6   879.4   508.1  876.81   527.7  863.59
   547.2  862.51   878.4  862.53   889.1   862.9   893.4  864.78   937.9  889.59
   947.7  892.37   957.4  898.13   967.2  901.21   996.5   915.2    1016  919.56
  1045.3  929.51  1084.4  938.19  1133.2  946.49  1250.4  957.71  1338.3  953.39
#Mann= 3 , 0 , 0
       0      .1       0   878.4    .045       0   893.4      .1       0
Bank Sta=878.4,893.4
XS Rating Curve= 0 ,0
Exp/Cntr=0.3,0.1

Type RM Length L Ch R = 1 ,9180    ,308.768,305.183,300.826
XS GIS Cut Line= 3
      1778391.64      339488.237      1778969.43      339925.514
     1779602.437      340439.578
#Sta/Elev= 30
       0 1042.64    19.6 1046.11      49 1046.09    58.8 1043.55    97.9 1023.35
   127.3 1003.77   146.9  988.54   166.5  980.71     186  964.83     235  936.26
   264.4   914.7   303.6  896.17   332.9   885.6   421.1  863.43   440.6   862.5
   749.3  862.71   764.3  864.96   783.6  878.83   803.2  887.31   862.2  891.24
   881.8  899.78   901.4  905.56   960.4   917.7   999.7  923.18  1176.5  937.52
  1363.2  957.12  1402.5   964.9  1451.6  971.07  1490.9  969.94  1540.1   965.6
#Mann= 3 , 0 , 0
       0      .1       0   749.3    .045       0   764.3      .1       0
Bank Sta=749.3,764.3
XS Rating Curve= 0 ,0
Exp/Cntr=0.3,0.1

Type RM Length L Ch R = 1 ,8874.9  ,542.466,534.507,527.32
XS GIS Cut Line= 3
     1778209.059      339848.593     1778791.611      340166.902
     1779467.904      340506.844
#Sta/Elev= 30
       0 1064.75    48.8 1032.23    68.3 1014.75    87.9 1002.39    97.6  994.33
   117.1   983.4   146.4  960.15   156.2  956.52   175.7  942.26   185.5  937.14
     205  921.61   234.3  904.64   244.1  899.65   292.9  886.15   312.4   878.4
   351.4  866.75   380.7  862.51   656.3  862.51   671.3  862.73   683.5  865.26
   693.3  872.53     713  881.98   732.7  888.75   791.6  892.07   870.3  907.26
   929.3  916.35  1086.5  929.16  1214.3  945.44  1322.5  956.11  1420.8   973.3
#Mann= 3 , 0 , 0
       0      .1       0   656.3    .045       0   671.3      .1       0
Bank Sta=656.3,671.3
XS Rating Curve= 0 ,0
Exp/Cntr=0.3,0.1

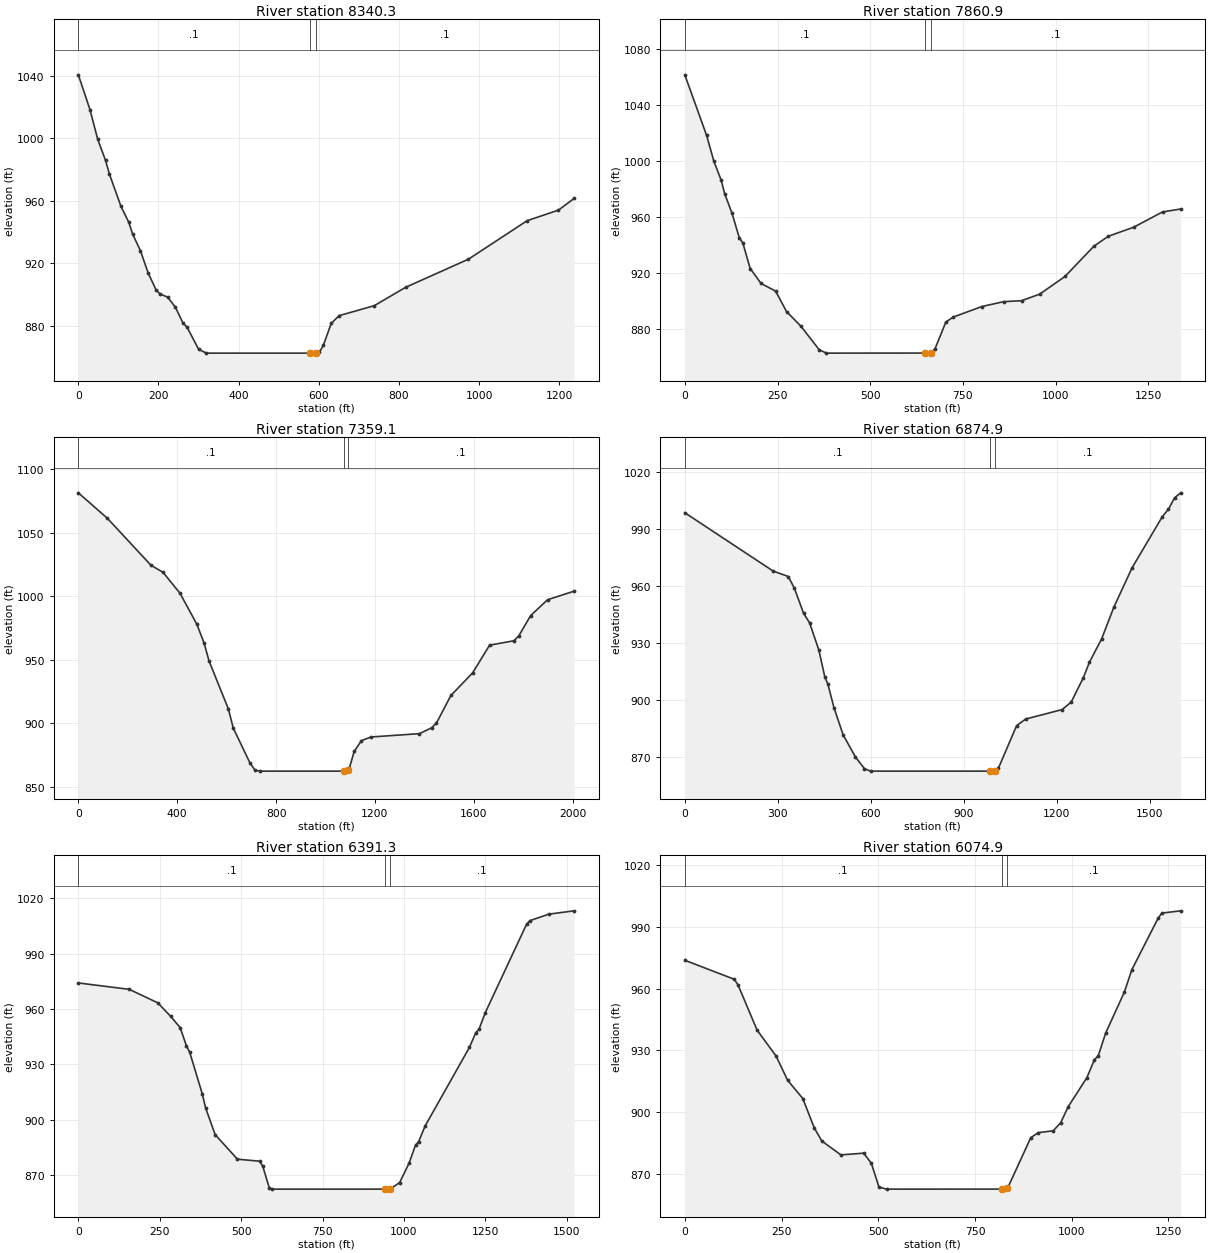
Type RM Length L Ch R = 1 ,8340.3  ,479.002,479.411,479.819
XS GIS Cut Line= 3
     1778106.174      340628.207     1778559.522      340666.949
     1779333.371      340780.715
#Sta/Elev= 30
       0 1040.76      29 1018.51    48.4  999.44    67.8  986.01    77.4  977.31
   106.5  956.43   125.9  946.31   135.5  938.74   154.9  928.16   174.3  913.79
   193.6  903.23   203.3  900.47   222.7  898.38     242  892.03   261.4  881.61
   271.1   879.2   300.1  864.99   319.5  862.51   577.7  862.51   592.7  862.57
   601.7  863.19   611.4  867.49     631  881.53   650.5  886.49   738.5  892.91
   816.8  904.68   973.2  922.64  1119.8  947.33  1198.1  954.12  1237.2   961.6
#Mann= 3 , 0 , 0
       0      .1       0   577.7    .045       0   592.7      .1       0
Bank Sta=577.7,592.7
XS Rating Curve= 0 ,0
Exp/Cntr=0.3,0.1

Type RM Length L Ch R = 1 ,7860.9  ,497.064,501.844,506.625
XS GIS Cut Line= 3
     1778017.447      341018.412     1778463.711      341131.462
     1779328.566      341275.604
#Sta/Elev= 30
       0 1061.79    58.8  1018.4    78.4   999.9    97.9  986.47   107.7  976.52
   127.3  962.67   146.9  945.08   156.7  941.25   176.3  923.07   205.7  912.36
   244.9  906.87   274.3  892.24   313.4  881.67   362.4  864.89     382  862.46
   648.3  862.51   663.3  862.54   674.7  865.52   703.9  884.66   723.4  888.24
   801.3  895.85   859.8  899.32   908.5  900.03   957.2  904.73  1025.4  917.39
  1103.3  939.08  1142.3  946.18  1210.5  952.64  1288.4  963.61  1337.1  965.68
#Mann= 3 , 0 , 0
       0      .1       0   648.3    .045       0   663.3      .1       0
Bank Sta=648.3,663.3
XS Rating Curve= 0 ,0
Exp/Cntr=0.3,0.1

Type RM Length L Ch R = 1 ,7359.1  ,482.262,484.238,486.727
XS GIS Cut Line= 3
     1777541.199        341270.8     1778532.017      341640.432
     1779415.052      341986.707
#Sta/Elev= 30
       0 1081.24   117.5 1061.23   293.8 1024.31   342.7 1018.79   411.3 1002.32
   479.8  977.84   509.2  962.97   528.8  949.07   607.1  911.34   626.7  896.43
   695.2  868.59   714.8  863.31   734.4  862.51  1074.9  862.51  1089.9  863.27
  1096.6  864.95  1116.2  878.05  1145.5   886.5  1184.6  889.35  1380.2  891.97
  1429.1  896.56  1448.7  900.25  1507.3  921.95  1595.3  939.76  1663.8  961.51
  1761.6  964.95  1781.1  968.54    1830  984.77  1898.5  997.21    2006 1003.97
#Mann= 3 , 0 , 0
       0      .1       0  1074.9    .045       0  1089.9      .1       0
Bank Sta=1074.9,1089.9
XS Rating Curve= 0 ,0
Exp/Cntr=0.3,0.1

Type RM Length L Ch R = 1 ,6874.9  ,487.175,483.601,479.515
XS GIS Cut Line= 3
     1777574.832      341684.008     1778463.456      342123.721
     1779001.843      342404.721
#Sta/Elev= 30
       0  998.69   284.7  967.95   333.8  965.07   353.4  958.87   382.8  945.77
   402.5  940.62   431.9   926.5   451.6  912.12   461.4  908.35     481  895.94
   510.5  881.65   549.7   870.1   579.2  863.84   598.8  862.51     984  862.51
     999  862.84  1011.1     864  1069.8  886.43  1099.2  889.96  1216.8  894.95
  1246.1  898.93  1285.3  911.82  1304.9  919.98  1344.1   932.2  1383.3  948.82
    1442   969.6    1540  996.68  1559.6 1000.52  1579.2 1006.52  1598.8 1009.17
#Mann= 3 , 0 , 0
       0      .1       0     984    .045       0     999      .1       0
Bank Sta=984,999
XS Rating Curve= 0 ,0
Exp/Cntr=0.3,0.1

Type RM Length L Ch R = 1 ,6391.3  ,312.206,316.399,319.448
XS GIS Cut Line= 3
     1777425.885      342303.821     1778358.006      342596.911
     1778881.724      342750.663
#Sta/Elev= 30
       0  974.08   156.3  970.63   244.3   963.3   283.4  956.03   312.7  949.94
   332.2  939.96     342  936.65   381.1  913.81   390.8  906.52   420.2  892.02
   488.6  878.71     557  877.62   566.7  874.78   586.3   863.3     596  862.51
   942.8  862.51   957.8  862.52   986.9  866.06  1016.1  876.66  1035.6  886.33
  1045.3  888.22  1064.8  896.57  1201.3  939.24  1220.8  947.18  1230.5  948.95
    1250  958.04  1376.7 1005.85  1386.5 1007.76    1445 1011.31  1522.9 1013.11
#Mann= 3 , 0 , 0
       0      .1       0   942.8    .045       0   957.8      .1       0
Bank Sta=942.8,957.8
XS Rating Curve= 0 ,0
Exp/Cntr=0.3,0.1

Type RM Length L Ch R = 1 ,6074.9  ,793.624,800,807.726
XS GIS Cut Line= 3
     1777449.909      342467.182      1778176.88      342860.303
     1778586.826      343057.707
#Sta/Elev= 30
       0  973.78   127.9  964.53   137.7  961.73   186.9  939.79   236.1  927.17
   265.6  915.48     305  906.55   334.5   892.3   354.2  885.92   403.4  879.15
   462.4     880   482.1   875.1   501.8  863.53   521.5  862.51     819  862.52
     834  862.87   894.2  887.52   913.6  889.97   952.3  890.87   971.7  894.84
     991   902.6  1039.4  916.75  1058.8  925.48  1068.5  927.28  1087.8   938.4
  1136.2  958.36  1155.6  969.25  1223.4  994.26  1233.1  996.71  1281.5  997.81
#Mann= 3 , 0 , 0
       0      .1       0     819    .045       0     834      .1       0
Bank Sta=819,834
XS Rating Curve= 0 ,0
Exp/Cntr=0.3,0.1

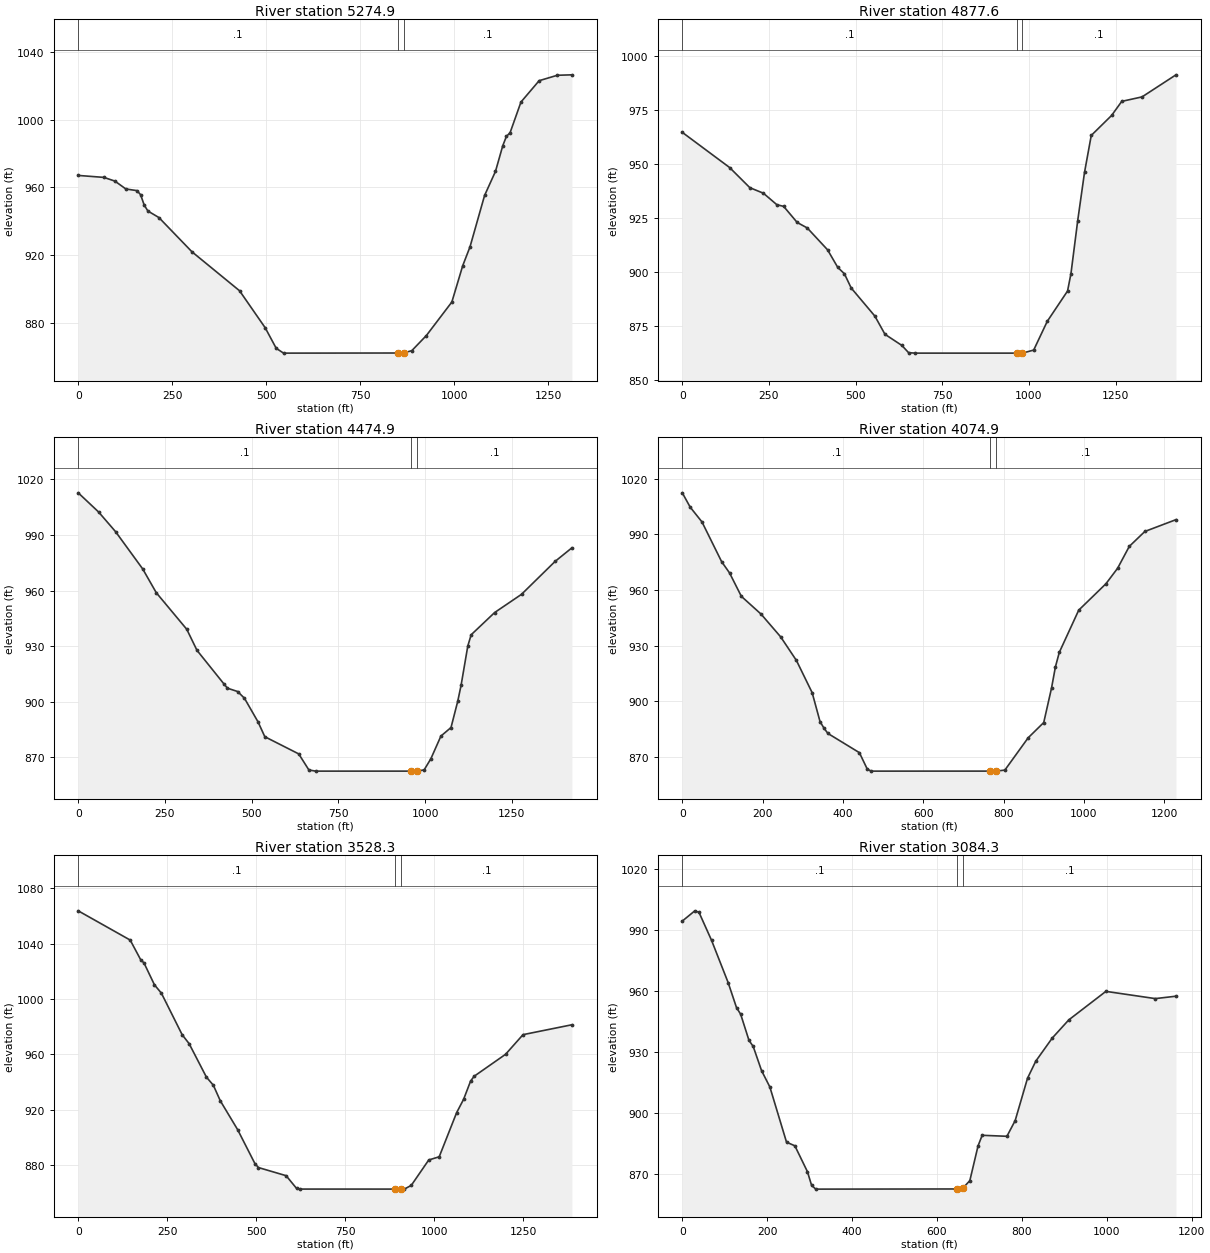
Type RM Length L Ch R = 1 ,5274.9  ,398.409,397.246,395.875
XS GIS Cut Line= 3
     1777031.895      342856.367     1777646.386      343456.086
     1777969.077      343776.859
#Sta/Elev= 30
       0   967.1    68.3  965.94    97.6  963.76   126.8  959.11   156.1  958.16
   165.9  955.78   175.6  949.63   185.4  946.14   214.7  942.29   302.5  922.15
   429.3  899.17   497.6  877.35   526.9  865.26   546.4  862.44   851.1  862.51
   866.1  862.53   887.7  863.91   926.4   872.8   994.2  892.54  1023.2  913.97
  1042.6   925.1  1081.3   955.3  1110.3  969.48  1129.7   984.6  1139.4   990.1
  1149.1  992.23  1178.1 1010.32  1226.5  1022.9  1274.9 1026.09  1313.6 1026.35
#Mann= 3 , 0 , 0
       0      .1       0   851.1    .045       0   866.1      .1       0
Bank Sta=851.1,866.1
XS Rating Curve= 0 ,0
Exp/Cntr=0.3,0.1

Type RM Length L Ch R = 1 ,4877.6  ,404.431,402.754,403.544
XS GIS Cut Line= 3
     1776615.165        343091.3     1777325.987      343699.785
     1777692.019      344023.554
#Sta/Elev= 30
       0  964.66   136.5  948.39   194.9  939.06   233.9  936.51   272.9  931.17
   292.4  930.42   331.4  922.98   360.6  920.42   419.1  910.32   448.4  902.22
   467.8  899.21   487.3  892.65   555.6  879.65   584.8  871.22   633.5  866.07
     653  862.71   672.5  862.51   966.4  862.51   981.4  862.51  1013.9  863.93
    1053  877.21  1111.6  891.25  1121.4  899.28  1140.9  923.83  1160.5   946.1
    1180  963.24  1238.7  972.48    1268     979  1326.6  981.07  1424.4  991.28
#Mann= 3 , 0 , 0
       0      .1       0   966.4    .045       0   981.4      .1       0
Bank Sta=966.4,981.4
XS Rating Curve= 0 ,0
Exp/Cntr=0.3,0.1

Type RM Length L Ch R = 1 ,4474.9  ,399.029,400,399.775
XS GIS Cut Line= 3
     1776263.135      343370.475     1777029.424      343962.553
     1777359.279      344275.955
#Sta/Elev= 30
       0 1012.78    58.7 1002.44   107.6  991.83   185.9  971.69     225  958.86
     313  939.09   342.4  927.74   420.6  909.49   430.4  907.28   459.7  905.49
   479.3  901.86   518.4  889.12     538  881.09   635.8  871.81   665.1  863.13
   684.7  862.51   960.9  862.51   975.9  862.51   997.4  863.17  1016.8   869.2
  1045.8  881.44  1074.9  886.06  1094.2  900.16  1103.9  908.81  1123.3  930.07
    1133  936.14  1200.7  948.14  1278.2  957.98    1375  975.75  1423.4  983.07
#Mann= 3 , 0 , 0
       0      .1       0   960.9    .045       0   975.9      .1       0
Bank Sta=960.9,975.9
XS Rating Curve= 0 ,0
Exp/Cntr=0.3,0.1

Type RM Length L Ch R = 1 ,4074.9  ,548.442,546.517,543.322
XS GIS Cut Line= 3
     1776123.797      343721.222     1776720.542      344214.233
     1777054.432      344523.332
#Sta/Elev= 30
       0 1012.36    19.6 1004.66      49  996.68      98  975.25   117.6  969.24
     147  956.63     196  947.07     245  934.77   284.1   922.1   323.3  904.75
   342.9  889.18   352.7  885.66   362.5  882.79   440.9  872.44   460.5  863.59
   470.3   862.5   766.6  862.51   781.6  862.51   803.1  863.06   861.2  880.47
   899.9  888.67   919.3  907.25     929  918.66   938.6  926.43     987  949.18
  1054.8  963.41  1083.8  971.74  1112.9  983.52  1151.6  991.55  1229.1  997.91
#Mann= 3 , 0 , 0
       0      .1       0   766.6    .045       0   781.6      .1       0
Bank Sta=766.6,781.6
XS Rating Curve= 0 ,0
Exp/Cntr=0.3,0.1

Type RM Length L Ch R = 1 ,3528.3  ,448.914,444.004,439.442
XS GIS Cut Line= 3
     1775633.713      344129.626     1776277.549      344566.858
     1776777.243      344912.801
#Sta/Elev= 30
       0 1063.76   145.9 1042.61   175.1 1028.52   184.8    1026     214 1010.25
   233.5 1004.21   291.8  974.16   311.3  967.72   359.9   943.5   379.4  937.61
   398.9  926.37   447.5  905.52   496.1  880.95   505.9  878.09   583.7   872.2
   612.9  863.04   622.6  862.52   890.3  862.51   905.3  862.49   915.5  862.48
   935.1   865.2   984.1  883.56  1013.5  885.87  1062.5  917.83  1082.1  927.49
  1101.7  940.67  1111.6  944.11  1199.8  959.99  1248.8   974.2    1386  981.35
#Mann= 3 , 0 , 0
       0      .1       0   890.3    .045       0   905.3      .1       0
Bank Sta=890.3,905.3
XS Rating Curve= 0 ,0
Exp/Cntr=0.3,0.1

Type RM Length L Ch R = 1 ,3084.3  ,214.009,209.48,204.519
XS GIS Cut Line= 3
      1775580.86      344811.901     1776179.522      345033.673
     1776661.929      345239.524
#Sta/Elev= 30
       0  994.39    29.5  999.43    39.3  998.69    68.8  984.95     108   964.1
   127.7  951.78   137.5  948.52   157.1  935.63     167  932.68   186.6  920.81
   206.3  912.69   245.5  885.55   265.2  883.75   294.7  871.04   304.5  864.34
   314.3  862.43   646.2  862.51   661.2  862.99   677.3   866.6   696.7  883.73
   706.4  888.93   764.7  888.44   784.1  896.16   813.2  917.01   832.7  925.43
   871.5  936.81   910.4  945.74   997.8  959.78  1114.3  956.22  1162.9   957.4
#Mann= 3 , 0 , 0
       0      .1       0   646.2    .045       0   661.2      .1       0
Bank Sta=646.2,661.2
XS Rating Curve= 0 ,0
Exp/Cntr=0.3,0.1

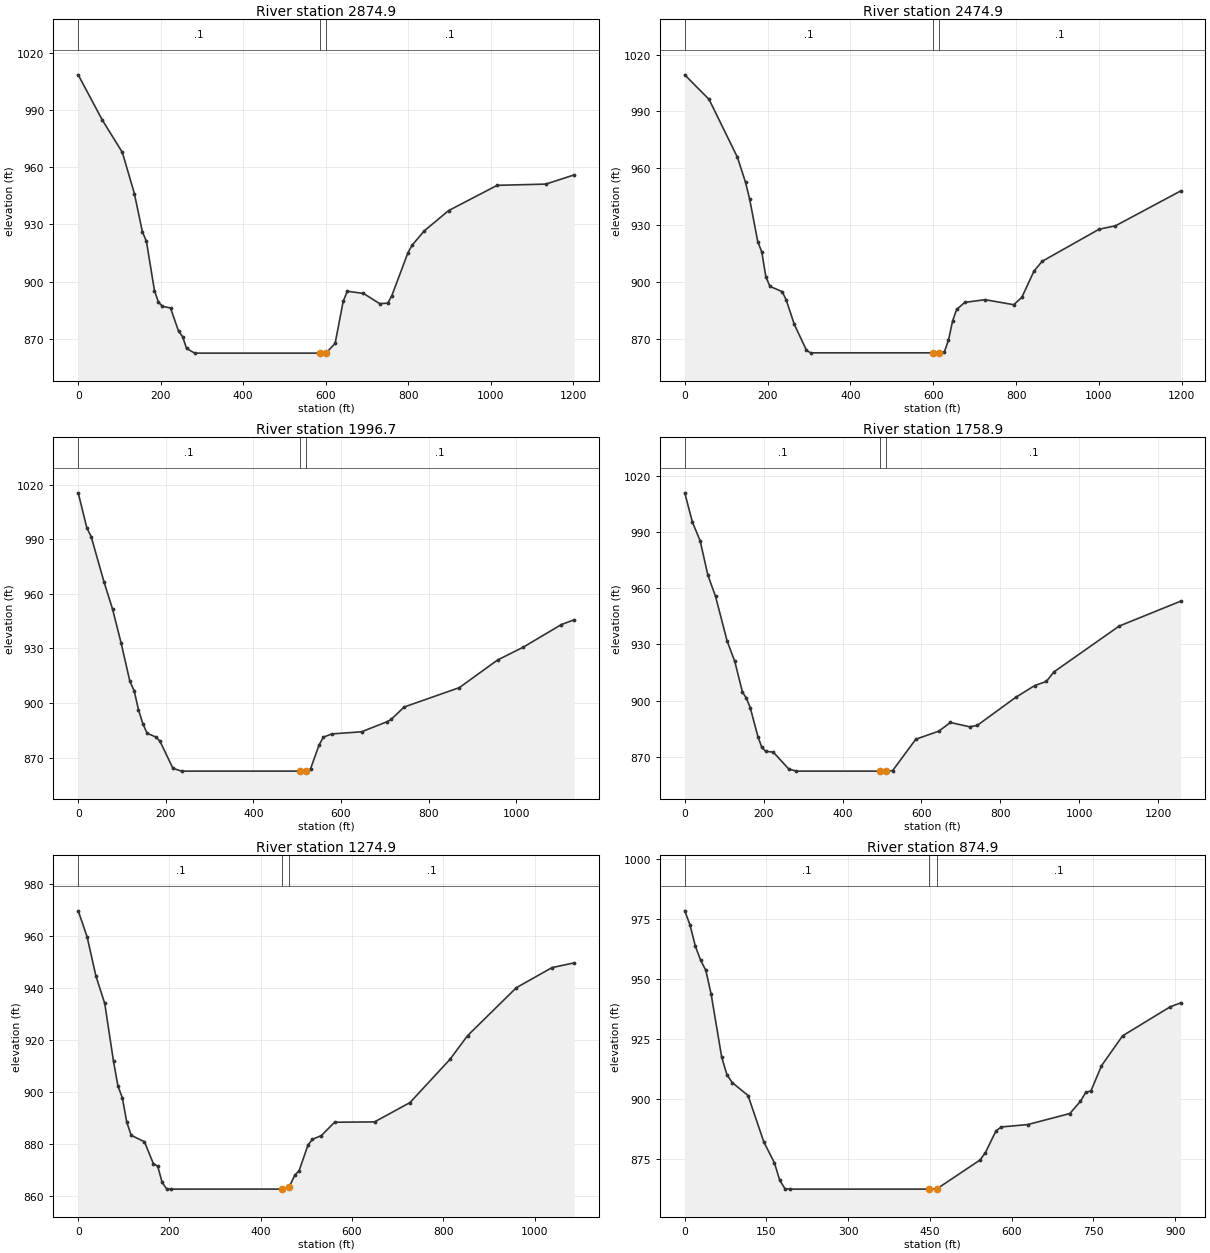
Type RM Length L Ch R = 1 ,2874.9  ,411.358,400,388.828
XS GIS Cut Line= 3
     1775547.227      345129.014     1776130.445      345239.187
     1776729.196      345350.033
#Sta/Elev= 30
       0 1008.46    58.4  984.76     107  967.81   136.2  946.19   155.7  926.07
   165.4  921.19   184.9   895.3   194.6  889.17   204.3  887.08   223.8  886.18
   243.3  874.04     253  871.19   262.7  865.02   282.2  862.51     586  862.51
     601  862.52     623  867.64   642.6  889.67   652.5  894.95   691.7  893.84
     731  888.46   750.7  888.72   760.5  892.63   799.8  915.27   809.6  919.08
   839.1  926.61     898  937.24  1015.9  950.51  1133.7  951.15  1202.5  955.96
#Mann= 3 , 0 , 0
       0      .1       0     586    .045       0     601      .1       0
Bank Sta=586,601
XS Rating Curve= 0 ,0
Exp/Cntr=0.3,0.1

Type RM Length L Ch R = 1 ,2474.9  ,492.122,478.154,464.381
XS GIS Cut Line= 3
     1775571.251      345816.094      1776148.43      345627.109
     1776709.977      345446.128
#Sta/Elev= 30
       0 1009.28    58.8  996.29   127.3  965.71   146.9  952.44   156.7   943.7
   176.3  921.22   186.1  915.68   195.9  902.62   205.7   897.6   235.1  894.84
   244.9  890.53   264.5  877.55   293.9  863.87   303.7  862.51   599.8  862.51
   614.8  862.39   617.2  862.35     627  863.08   636.8  869.17   646.7  879.31
   656.5  885.41   676.2  889.15   725.3  890.56   794.2  887.92   813.8  891.75
   843.3  905.67     863  910.83  1000.7  927.79    1040  929.56  1197.3  947.96
#Mann= 3 , 0 , 0
       0      .1       0   599.8    .045       0   614.8      .1       0
Bank Sta=599.8,614.8
XS Rating Curve= 0 ,0
Exp/Cntr=0.3,0.1

Type RM Length L Ch R = 1 ,1996.7  ,243.347,237.822,232.103
XS GIS Cut Line= 3
     1776080.555      346431.102     1776385.223         346021.
     1776762.829      345527.809
#Sta/Elev= 30
       0 1015.61    19.6  996.42    29.5  991.57    58.9  966.61    78.6  951.47
    98.2  932.73   117.9  911.94   127.7  906.75   137.5  896.37   147.4  888.71
   157.2  883.34   176.8  881.34   186.7  878.98   216.1  864.08   235.8  862.51
   505.4  862.51   520.4  862.51   530.3  863.73   549.7  876.78   559.4  881.16
   578.8  882.97   646.8  884.15     705  889.69   714.7     891   743.8  897.76
     870  908.44   957.3  923.64  1015.6  930.65  1102.9  943.13    1132  945.75
#Mann= 3 , 0 , 0
       0      .1       0   505.4    .045       0   520.4      .1       0
Bank Sta=505.4,520.4
XS Rating Curve= 0 ,0
Exp/Cntr=0.3,0.1

Type RM Length L Ch R = 1 ,1758.9  ,490.053,484.024,479.586
XS GIS Cut Line= 3
     1776344.816      346628.097     1776609.531      346083.725
     1776887.753      345494.175
#Sta/Elev= 30
       0 1010.82    19.5  995.16    39.1  985.23    58.6  967.01    78.1  955.63
   107.4  931.89   126.9  920.95   146.4  904.56   156.2  901.46     166  896.37
   185.5  880.93   195.3  875.23     205  873.13   224.6  872.61   263.6  863.66
   283.1  862.51   495.5  862.51   510.5  862.51   527.2  862.82   585.8  879.52
   644.2  883.82   673.4  888.43   722.1  886.14   741.5  886.87   838.8  901.79
   887.5  908.14   916.7  910.28   936.1   915.4  1101.5  939.82  1257.2  953.07
#Mann= 3 , 0 , 0
       0      .1       0   495.5    .045       0   510.5      .1       0
Bank Sta=495.5,510.5
XS Rating Curve= 0 ,0
Exp/Cntr=0.3,0.1

Type RM Length L Ch R = 1 ,1274.9  ,402.199,400,396.105
XS GIS Cut Line= 3
     1776928.366      346765.094     1777008.602      346317.224
     1777166.428      345705.584
#Sta/Elev= 30
       0  969.53    19.4  959.62    38.7  944.52    58.1  933.95    77.4  911.61
    87.1  902.15    96.8  897.56   106.5  888.17   116.2   883.2   145.2  880.72
   164.6  872.34   174.3   871.3   183.9  865.09   193.6  862.65   203.3  862.51
   447.5  862.53   462.5  863.36   474.4   867.8   484.2  869.66   503.6  879.48
   513.3  881.68   532.7  883.09   561.9  888.24   649.4  888.36   727.1   895.8
   814.6   912.4   853.4  921.56   960.3  939.99  1038.1  947.68  1086.7  949.52
#Mann= 3 , 0 , 0
       0      .1       0   447.5    .045       0   462.5      .1       0
Bank Sta=447.5,462.5
XS Rating Curve= 0 ,0
Exp/Cntr=0.3,0.1

Type RM Length L Ch R = 1 ,874.9   ,488.601,491.413,494.008
XS GIS Cut Line= 3
     1777368.391       346825.18     1777404.561       346371.62
     1777440.732       345918.06
#Sta/Elev= 30
       0  978.33     9.7  972.43    19.4   963.7      29  957.86    38.7  953.55
    48.4  943.72    67.8  917.45    77.4  910.12    87.1  906.86   116.2  901.47
   145.2   882.1   164.6  873.45   174.3  866.22   183.9   862.7   193.6  862.51
   447.5  862.51   462.5   862.6   542.1  874.66   551.8  877.75   571.2  886.75
   580.9  888.38   629.3  889.38   706.7  893.97   726.1  899.05   735.7  902.73
   745.4  903.38   764.8  913.85   803.5  926.31   890.6  938.35     910  940.02
#Mann= 3 , 0 , 0
       0      .1       0   447.5    .045       0   462.5      .1       0
Bank Sta=447.5,462.5
XS Rating Curve= 0 ,0
Exp/Cntr=0.3,0.1

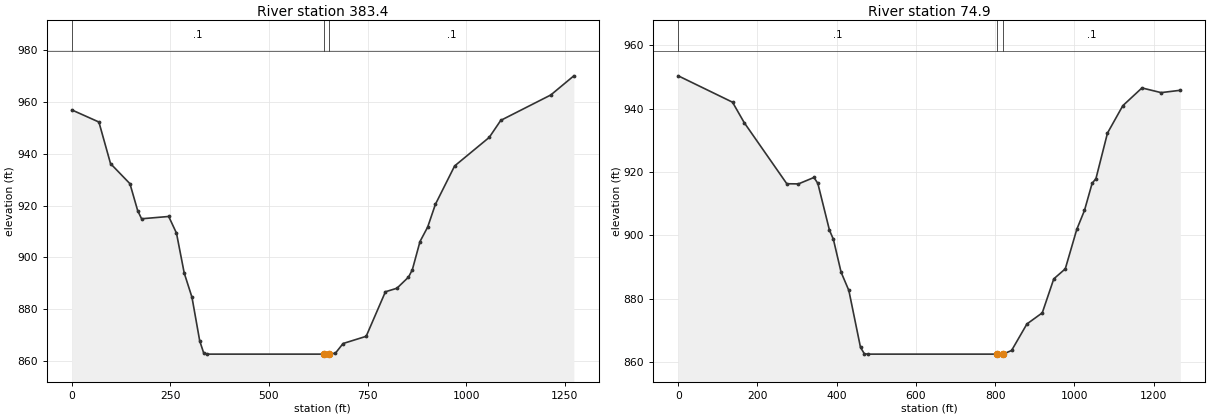
Type RM Length L Ch R = 1 ,383.4   ,303.585,308.587,309.306
XS GIS Cut Line= 3
     1777757.413      347079.743     1777891.089       346434.73
     1778002.455      345830.508
#Sta/Elev= 30
       0  956.99    68.8   952.3    98.3  936.21   147.5  928.44   167.1  918.03
     177  914.87   245.8  915.76   265.5  909.32   285.1  893.91   304.8   884.5
   324.4  867.66   334.3  863.03   344.1  862.51   638.5  862.51   653.5  862.52
   668.5  862.88     688  866.62   746.5   869.4   795.3  886.63   824.5     888
   853.8   892.3   863.5  895.12     883  906.07   902.5  911.68     922  920.45
   970.8  935.31  1058.6  946.36  1087.8  952.94  1214.6  962.76  1273.1  970.17
#Mann= 3 , 0 , 0
       0      .1       0   638.5    .045       0   653.5      .1       0
Bank Sta=638.5,653.5
XS Rating Curve= 0 ,0
Exp/Cntr=0.3,0.1

Type RM Length L Ch R = 1 ,74.9    ,77.3,74.854,76.908
XS GIS Cut Line= 3
     1777853.508      347252.714     1778188.769      346512.836
     1778291.144      346069.683
#Sta/Elev= 30
       0  950.32     137     942   166.4  935.57     274  916.27   303.4  916.22
   342.5  918.25   352.3  916.39   381.7  901.59   391.5  898.76     411  888.36
   430.6  882.59     460  864.63   469.8  862.61   479.5  862.51   804.8  862.51
   819.8  862.52   841.3  863.66     880  872.03   918.7  875.53   947.8  886.26
   976.8  889.42  1005.8  901.87  1025.2  907.84  1044.5  916.38  1054.2   917.9
  1083.3  932.26    1122   940.9  1170.3   946.5  1218.7  945.02  1267.1  945.76
#Mann= 3 , 0 , 0
       0      .1       0   804.8    .045       0   819.8      .1       0
Bank Sta=804.8,819.8
XS Rating Curve= 0 ,0
Exp/Cntr=0.3,0.1

Chan Stop Cuts=-1
Use User Specified Reach Order=0